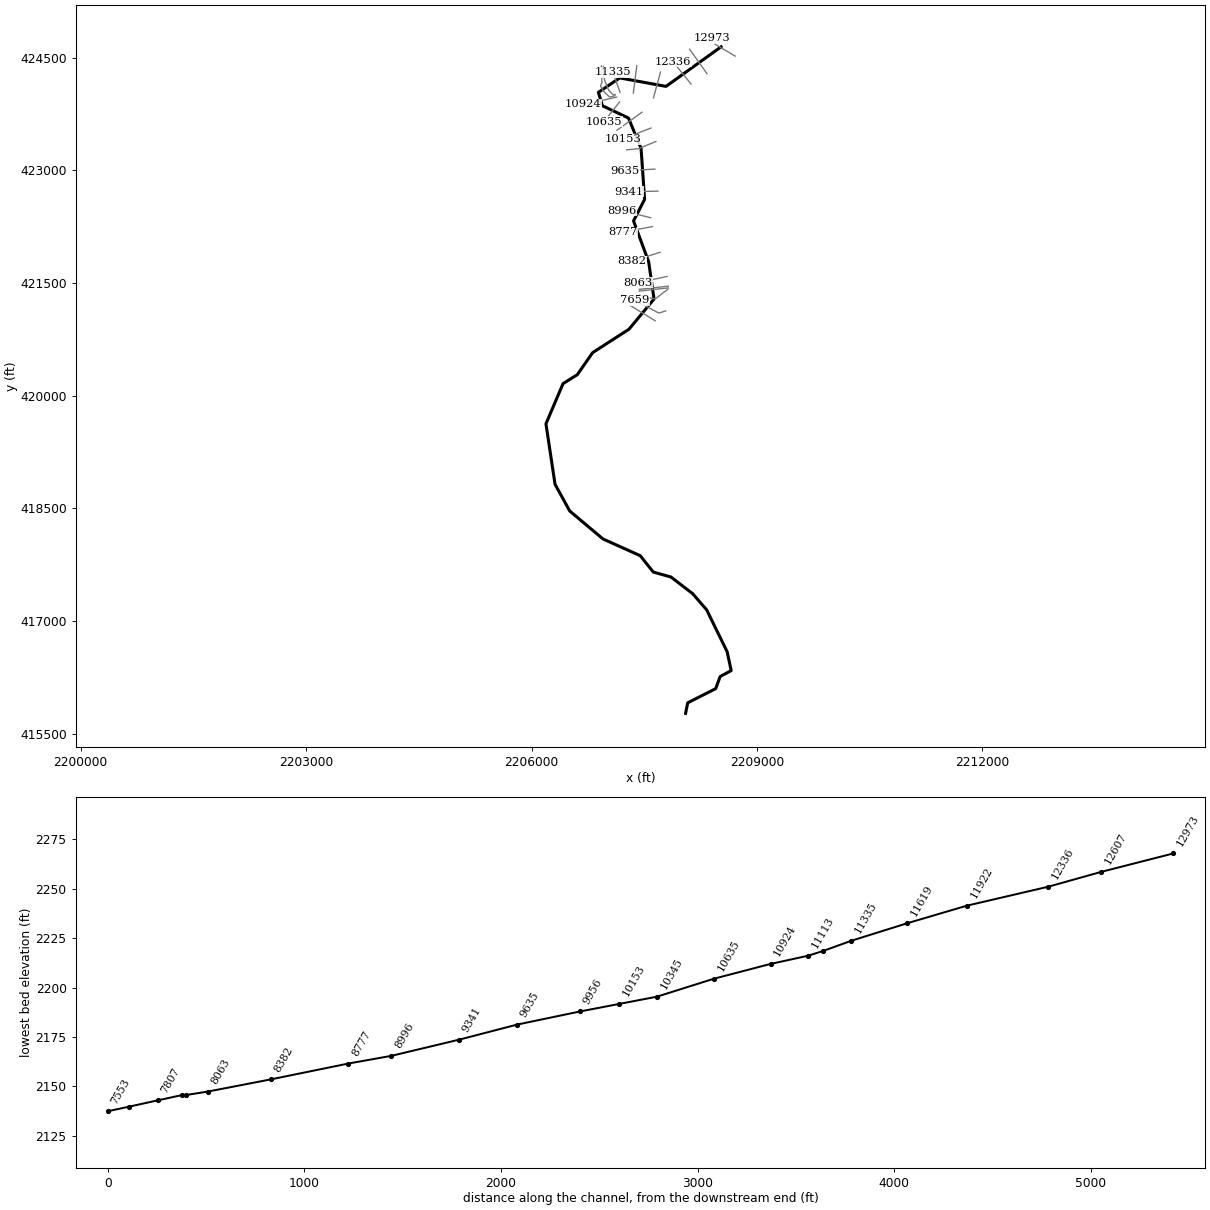
--- STVNSHLRN.prj (project) ---

Proj Title=STVNSHLRN
Current Plan=p01
Default Exp/Contr=0,0
English Units
Geom File=g01
Flow File=f01
Plan File=p01
Background Map Layer=Inundation Boundary (01pct Value_0)
Background Map Layer=Inundation Boundary (01pct Value_0)
Background Map Layer=Inundation Boundary (01pct Value_0)
BEGIN DESCRIPTION:
----------MODEL BY WOOD PLC 2021----------
Stream Name: Stevens Hole Run
Flood Zone: Enhanced Approximate
Pocahontas County, WV
HEC-RAS Version: RAS 6.1
Vertical Datum: NAVD88
Projection: NAD 1983 StatePlane West Virginia S FIPS 4702 (US Feet)
Terrain: 1-meter LIDAR (FEMA Region III 3DEP collected 2016-2018)
Land Use: 2019 NLCD
Hydrologic Method:
WV SIR2010-5033 regression equations
Model Notes:
Normal depth tie in to Greenbrier River
END DESCRIPTION:
DSS Export Rating Curves= 0
DSS Export Rating Curve Sorted= 0
DSS Export Volume Flow Curves= 0
DXF OffsetX= 0
DXF OffsetY= 0
DXF ScaleX= 0
DXF ScaleY= 0

--- STVNSHLRN.p01 (plan) ---

Plan Title=Floodplain
Program Version=6.10
Short Identifier=Floodplain
Geom File=g01
Flow File=f01
Subcritical Flow
K Sum by GR= 0
Std Step Tol= 0.01
Critical Tol= 0.01
Num of Std Step Trials= 20
Max Error Tol= 0.3
Flow Tol Ratio= 0.001
Split Flow NTrial= 30
Split Flow Tol= 0.02
Split Flow Ratio= 0.02
Log Output Level= 0
Friction Slope Method= 1
Unsteady Friction Slope Method= 2
Unsteady Bridges Friction Slope Method= 1
Parabolic Critical Depth
Global Vel Dist= 0 , 0 , 0
Global Log Level= 0
CheckData=True
Encroach Param=-1 ,0,0, 0
Mapping Interval=1HOUR
Computation Time Step Use Courant=        0
Computation Time Step Use Time Series=    0
Computation Time Step Count To Double=0
Computation Time Step Max Doubling=0
Computation Time Step Max Halving=0
Computation Time Step Residence Courant=0
Run HTab= 0
Run UNet= 0
Run Sediment= 0
Run PostProcess= 0
Run WQNet= 0
Run RASMapper=-1
UNET Theta= 0
UNET Theta Warmup= 0
UNET ZTol= 0
UNET ZSATol= 0
UNET MxIter= 0
UNET Max Iter WO Improvement= 0
UNET MaxInSteps= 0
UNET DtIC= 0
UNET DtMin= 0
UNET MaxCRTS= 0
UNET WFStab= 0
UNET SFStab= 0
UNET WFX= 1
UNET SFX= 1
UNET Gravity=32.174
UNET 1D Methodology=Finite Difference
UNET DSS MLevel= 1
UNET Pardiso=0
UNET DZMax Abort= 0
UNET Use Existing IB Tables= 0
UNET Froude Reduction=False
UNET Froude Limit= 0
UNET Froude Power= 0
UNET D1 Cores= 0
UNET WindReference=Eulerian
UNET WindDragFormulation=Hsu (1988)
UNET D2 Coriolis=0
UNET D2 Cores= 0
UNET D2 Theta= 1
UNET D2 Theta Warmup= 1
UNET D2 Z Tol= 0.01
UNET D2 Volume Tol= 0.01
UNET D2 Max Iterations= 20
UNET D2 Equation= 0
UNET D2 RampUpFraction=0.1
UNET D2 TimeSlices= 1
UNET D2 Turbulence Formulation=Non-Conservative (original)
UNET D2 Eddy Viscosity=0.3
UNET D2 Transverse Eddy Viscosity=0.1
UNET D2 Smagorinsky Mixing=0
UNET D2 BCVolumeCheck=0
UNET D2 Cores=0
UNET D2 SolverType=PARDISO (Direct)
UNET D2 Minimum Iterations= 2147483647
UNET D2 Maximum Iterations= 2147483647
UNET D2 Restart Number= 10
UNET D2 Relaxation Coeff=1.3
UNET D2 SOR Precondition Iterations= 10
UNET D2 ILUT Maximum Fill= 8
UNET D2 ILUT Tolerance=1E-08
UNET D1D2 MaxIter= 0
UNET D1D2 ZTol=0.01
UNET D1D2 QTol=0.1
UNET D1D2 MinQTol=1
Write IC File= 0
Write IC File at Fixed DateTime=0
Write IC File at Sim End=0
Echo Input=False
Echo Parameters=False
Echo Output=False
Write Detailed= 0
HDF Write Warmup=0
HDF Write Time Slices=0
HDF Flush=0
HDF Compression= 1
HDF Chunk Size= 1
HDF Spatial Parts= 1
HDF Use Max Rows=0
HDF Fixed Rows= 1
Calibration Method= 0
Calibration Iterations= 20
Calibration Max Change=0.05
Calibration Tolerance=0.2
Calibration Maximum=1.5
Calibration Minimum=0.5
Calibration Optimization Method= 1
WQ AD Non Conservative
WQ ULTIMATE=-1
WQ Max Comp Step=1HOUR
WQ Output Interval=15MIN
WQ Output Selected Increments= 0
WQ Output face flow=0
WQ Output face velocity=0
WQ Output face area=0
WQ Output face dispersion=0
WQ Output cell volume=0
WQ Output cell surface area=0
WQ Output cell continuity=0
WQ Output cumulative cell continuity=0
WQ Output face conc=0
WQ Output face dconc_dx=0
WQ Output face courant=0
WQ Output face peclet=0
WQ Output face adv mass=0
WQ Output face disp mass=0
WQ Output cell mass=0
WQ Output cell source sink temp=0
WQ Output nsm pathways=0
WQ Output nsm derived pathways=0
WQ Create Restart=0
WQ Fixed Restart=0
WQ System Summary=0
WQ Write To DSS=0
Sorting and Armoring Iterations= 10
XS Update Threshold= 0.02
Bed Roughness Predictor= 0
Hydraulics Update Threshold= 0.02
Energy Slope Method= 1
Volume Change Method= 1
Sediment Retention Method= 0
Sediment TS Multiplier= 1
Warm Up Method= 0
XS Weighting Method= 0
Number of US Weighted Cross Sections= 1
Number of DS Weighted Cross Sections= 1
Upstream XS Weight=0
Main XS Weight=1
Downstream XS Weight=0
Number of DS XS's Weighted with US Boundary= 1
Upstream Boundary Weight= 1
Weight of XSs Associated with US Boundary= 0
Number of US XS's Weighted with DS Boundary= 1
Downstream Boundary Weight= 0.5
Weight of XSs Associated with DS Boundary= 0.5
Percentile Method= 0
Sediment Output Level= 3
Mass or Volume Output= 0
Output Increment Type= 1
Profile and TS Output Increment= 1
Transport Output Increment 1
XS Output Flag= 0
XS Output Increment= 10
Read HDF5 Sediment Hotstart= 0
Sediment Hotstart Type= 0
Write Gradation File= 0
Read Gradation Hotstart= 0
Write HDF5 File= 1
Write Binary Output= 1
Write DSS Sediment File= 0
DSS Sediment Output Type= 1
SV Curve= 0
Specific Gage Flag= 0
Subcell Erosion Methods= 0
Subcell Deposition Methods= 0
Advection Scheme= 1
Matrix Solver= 0
Implicit Weighting Factor= 1
Maximum Outer Loop Convergence Iterations= 5
Convergence Maximum Absolute= 0.001
Convergence RMSE= 0.0001
Grain Fractions Max Abs Error= 0.001
Max Subgrid Regions= 1
Max Subgrid Length Scale= 3.402823E+38
Initial Layer Thickness= 3.402823E+38
Min Layer Thickness= 3.402823E+38
Max Layer Thickness= 3.402823E+38
Number of Layers= 5

--- STVNSHLRN.f01 (steady flow) ---

Flow Title=Flow
Program Version=6.10
Number of Profiles= 6
Profile Names=01pct,10pct,04pct,02pct,0_2pct,01plus
River Rch & RM=STVNSHLRN,Main            ,12973
     524     276     368     444     734     776
River Rch & RM=STVNSHLRN,Main            ,11619
     584     309     411     495     816     864
River Rch & RM=STVNSHLRN,Main            ,9956
     662     352     467     561     922     979
River Rch & RM=STVNSHLRN,Main            ,8996
     747     399     528     634    1040    1110
River Rch & RM=STVNSHLRN,Main            ,5400
     833     446     590     707    1150    1230
Boundary for River Rch & Prof#=STVNSHLRN,Main            , 1
Up Type= 0
Dn Type= 3
Dn Slope=0.00685
Boundary for River Rch & Prof#=STVNSHLRN,Main            , 2
Up Type= 0
Dn Type= 3
Dn Slope=0.00685
Boundary for River Rch & Prof#=STVNSHLRN,Main            , 3
Up Type= 0
Dn Type= 3
Dn Slope=0.00685
Boundary for River Rch & Prof#=STVNSHLRN,Main            , 4
Up Type= 0
Dn Type= 3
Dn Slope=0.00685
Boundary for River Rch & Prof#=STVNSHLRN,Main            , 5
Up Type= 0
Dn Type= 3
Dn Slope=0.00685
Boundary for River Rch & Prof#=STVNSHLRN,Main            , 6
Up Type= 0
Dn Type= 3
Dn Slope=0.00685
DSS Import GetInterval= 0
DSS Import GetPeak= 0
DSS Import FillOption= 0

--- STVNSHLRN.g01 (geometry) ---

Geom Title=Geometry
Program Version=6.10

River Reach=STVNSHLRN       ,Main
Reach XY= 30
     2208522.086      424646.512     2207789.334      424119.947
2207173.05680135 424232.57566586     2206889.815      424040.833
     2206942.553      423862.267     2207289.615      423698.555
2207457.38225691423293.4155219222207504.50446707422615.490675857
2207356.95513528422328.4128140042207558.31067866421784.335096779
     2207629.744      421288.1422207296.43801769420886.116371068
2206812.81085981420574.1089369432206608.34504955420280.375702723
2206419.10079429420161.5665107952206191.58874898419626.485046308
     2206312.598       418820.76     2206507.988       418465.42
     2206949.336      418093.955      2207446.11      417870.043
     2207619.629      417652.392     2207855.166      417586.278
     2208143.057      417365.371     2208329.695      417150.011
     2208602.519      416592.015     2208656.547      416339.936
2208509.91706567416261.3058754232208450.45269852416099.890228852
      2208077.96       415911.07     2208049.669      415770.469

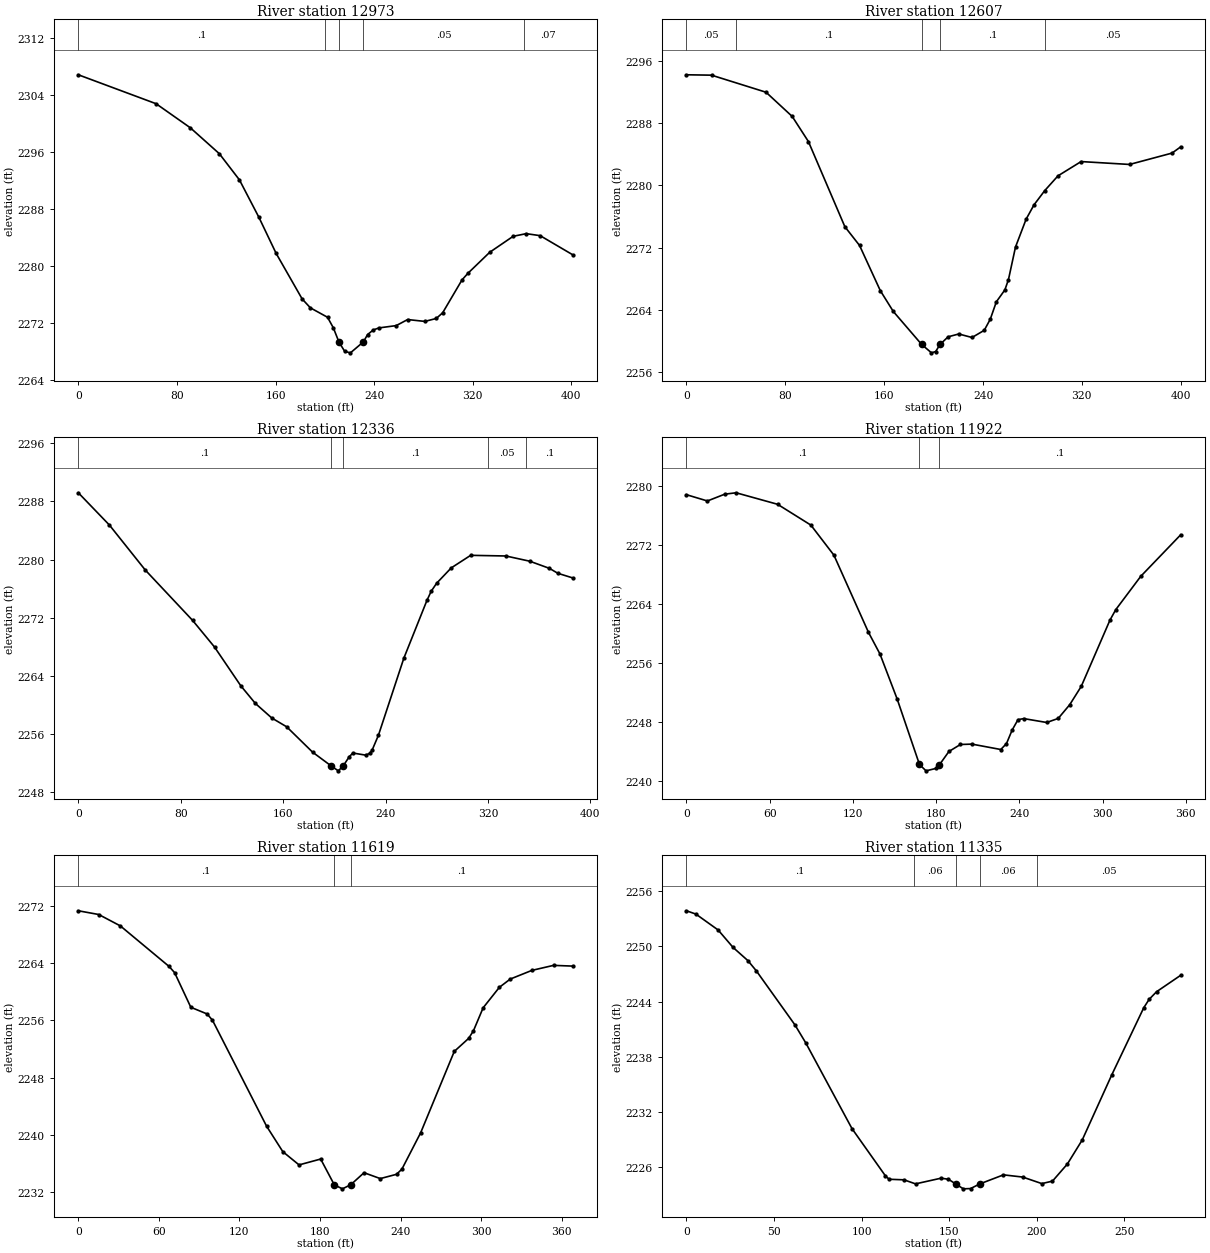
Type RM Length L Ch R = 1 ,12973   ,366,366,366
XS GIS Cut Line= 3
2208710.60491882424523.0505512832208442.13719458424680.598715774
2208399.74755391424759.726045025
#Sta/Elev= 30
       0 2306.79    63.1 2302.73    90.9 2299.35   114.4 2295.72   130.7 2292.05
   146.5  2286.8   160.5 2281.73   181.6 2275.34   188.3 2274.09   202.2 2272.77
   206.9 2271.29   211.5 2269.28   216.2 2267.97   220.8 2267.78   231.3 2269.32
   234.7 2270.35   239.4    2271     244 2271.28   257.9  2271.6   267.2 2272.45
   281.1 2272.19   290.4  2272.6   295.6  2273.4   311.3 2278.01   316.1 2278.94
   333.8 2281.89   352.8 2284.13   363.4  2284.5   374.7 2284.22     401 2281.55
#Mann= 5 ,-1,0
       0      .1       0     200     .05       0   211.5    .045       0
   231.3     .05       0  361.28     .07       0
Bank Sta=211.5,231.3
XS Rating Curve= 0 ,0
Exp/Cntr(USF)=0,0
Exp/Cntr=0.3,0.1

Type RM Length L Ch R = 1 ,12607   ,269.8,270.5,270.7
XS GIS Cut Line= 2
 2208334.9061268424288.6302247622208103.52464812424614.916312921
#Sta/Elev= 30
       0 2294.17    20.3 2294.12    64.4 2291.93    85.6 2288.82    98.7  2285.6
   128.2 2274.67   140.1 2272.26   156.9 2266.46   167.4 2263.79  190.342259.559
   198.3 2258.48   201.7 2258.65   205.3 2259.57   211.8 2260.54   220.4  2260.9
   231.1 2260.45     241 2261.37   245.9  2262.8   250.8 2265.03   257.7 2266.56
   260.6 2267.88   266.3 2272.06   274.9 2275.64   281.3 2277.48     290 2279.31
   300.7  2281.2   319.4 2283.03   358.6 2282.66     393 2284.12     400 2284.92
#Mann= 5 ,-1,0
       0     .05       0      40      .1       0  190.34    .045       0
   205.3      .1       0     290     .05       0
Bank Sta=190.34,205.3
XS Rating Curve= 0 ,0
Exp/Cntr(USF)=0,0
Exp/Cntr=0.3,0.1

Type RM Length L Ch R = 1 ,12336   ,426.8,414.5,405.2
XS GIS Cut Line= 2
2208122.81754477424150.2684627762207881.01269394424451.226129971
#Sta/Elev= 30
       0 2289.18    24.3 2284.74    52.3 2278.56    89.3 2271.63   106.4 2267.97
   126.9 2262.65   138.3 2260.22   151.1 2258.22   162.8    2257     183 2253.52
   197.4 2251.64   203.1 2250.95  206.94 2251.63   211.6 2252.88   214.5  2253.4
   224.4 2253.11   227.7 2253.35   229.5 2253.79   234.4 2255.82   254.3 2266.44
   272.4 2274.41   275.7 2275.65   279.9 2276.74   291.3 2278.85   306.5 2280.58
     334 2280.49   352.7 2279.77     368 2278.79   374.6 2278.11   386.1 2277.48
#Mann= 5 ,-1,0
       0      .1       0   197.4    .045       0  206.94      .1       0
     320     .05       0     350      .1       0
Bank Sta=197.4,206.94
XS Rating Curve= 0 ,0
Exp/Cntr(USF)=0,0
Exp/Cntr=0.3,0.1

Type RM Length L Ch R = 1 ,11922   ,301.4,302.7,304.4
XS GIS Cut Line= 2
2207622.08723972423966.5922229442207715.72383998424310.319350449
#Sta/Elev= 30
       0 2278.76    15.1 2277.91    27.6 2278.83    35.8 2279.02    65.7 2277.46
    89.7 2274.64   106.3 2270.57   131.2 2260.12   139.5 2257.18   151.9 2251.08
  167.982242.212   172.7 2241.35   179.7 2241.67182.40182242.179   189.2 2243.97
   197.5 2244.92   205.8 2244.97   226.6 2244.24   230.7 2245.04   234.8 2246.88
     239 2248.28   243.1 2248.43   259.7  2247.9     268 2248.45   276.3 2250.31
   284.6 2252.79   305.3 2261.77   309.5 2263.19   327.5  2267.7   356.3 2273.33
#Mann= 3 ,-1,0
       0      .1       0  167.98    .045       0182.4018      .1       0
Bank Sta=167.98,182.4018
XS Rating Curve= 0 ,0
Exp/Cntr(USF)=0,0
Exp/Cntr=0.3,0.1

Type RM Length L Ch R = 1 ,11619   ,278.6,284,286.9
XS GIS Cut Line= 2
2207354.14680769424030.090757354 2207400.6111669424395.281190972
#Sta/Elev= 30
       0  2271.3    15.2 2270.78    31.3 2269.19    67.6 2263.53    71.7 2262.67
    83.8 2257.83    95.9  2256.9    99.9 2256.03   140.2 2241.24   152.3 2237.68
   164.4 2235.83   180.5 2236.65   190.6 2233.07   190.6 2233.05   196.7 2232.49
  202.932233.067   212.8 2234.74   224.9 2233.92     237 2234.52     241 2235.24
     255 2240.33     280 2251.67   290.7 2253.49   294.3 2254.56   301.5 2257.76
   313.6 2260.62   321.7 2261.77   337.8 2262.98   353.9 2263.68   368.1 2263.58
#Mann= 3 ,-1,0
       0      .1       0   190.6    .045       0  202.93      .1       0
Bank Sta=190.6,202.93
XS Rating Curve= 0 ,0
Exp/Cntr(USF)=0,0
Exp/Cntr=0.3,0.1

Type RM Length L Ch R = 1 ,11335   ,142.2,143.2,143
BEGIN DESCRIPTION:
Structure XS 4
END DESCRIPTION:
XS GIS Cut Line= 2
2207178.04657404424040.1224922472207084.01385652424306.156258924
#Sta/Elev= 30
       0 2253.87     5.4 2253.51    18.1 2251.78    26.6 2249.89    35.1 2248.45
    39.9 2247.34    61.9 2241.48    68.1 2239.52    94.5  2230.2   113.6 2225.06
   115.7 2224.69   124.2 2224.63   130.8 2224.19   145.4 2224.81   149.6 2224.69
   153.9 2224.16   158.1 2223.65   162.2 2223.68   167.62224.194     181 2225.17
     192 2224.93   202.9 2224.22     209 2224.49   217.5 2226.35     226 2228.97
   242.9 2236.06   261.1 2243.33   264.2 2244.25   268.4 2245.07   282.2 2246.86
#Mann= 5 ,-1,0
       0      .1       0     130     .06       0   153.9    .045       0
   167.6     .06       0     200     .05       0
Bank Sta=153.9,167.6
XS Rating Curve= 0 ,0
Exp/Cntr(USF)=0,0
Exp/Cntr=0.5,0.3

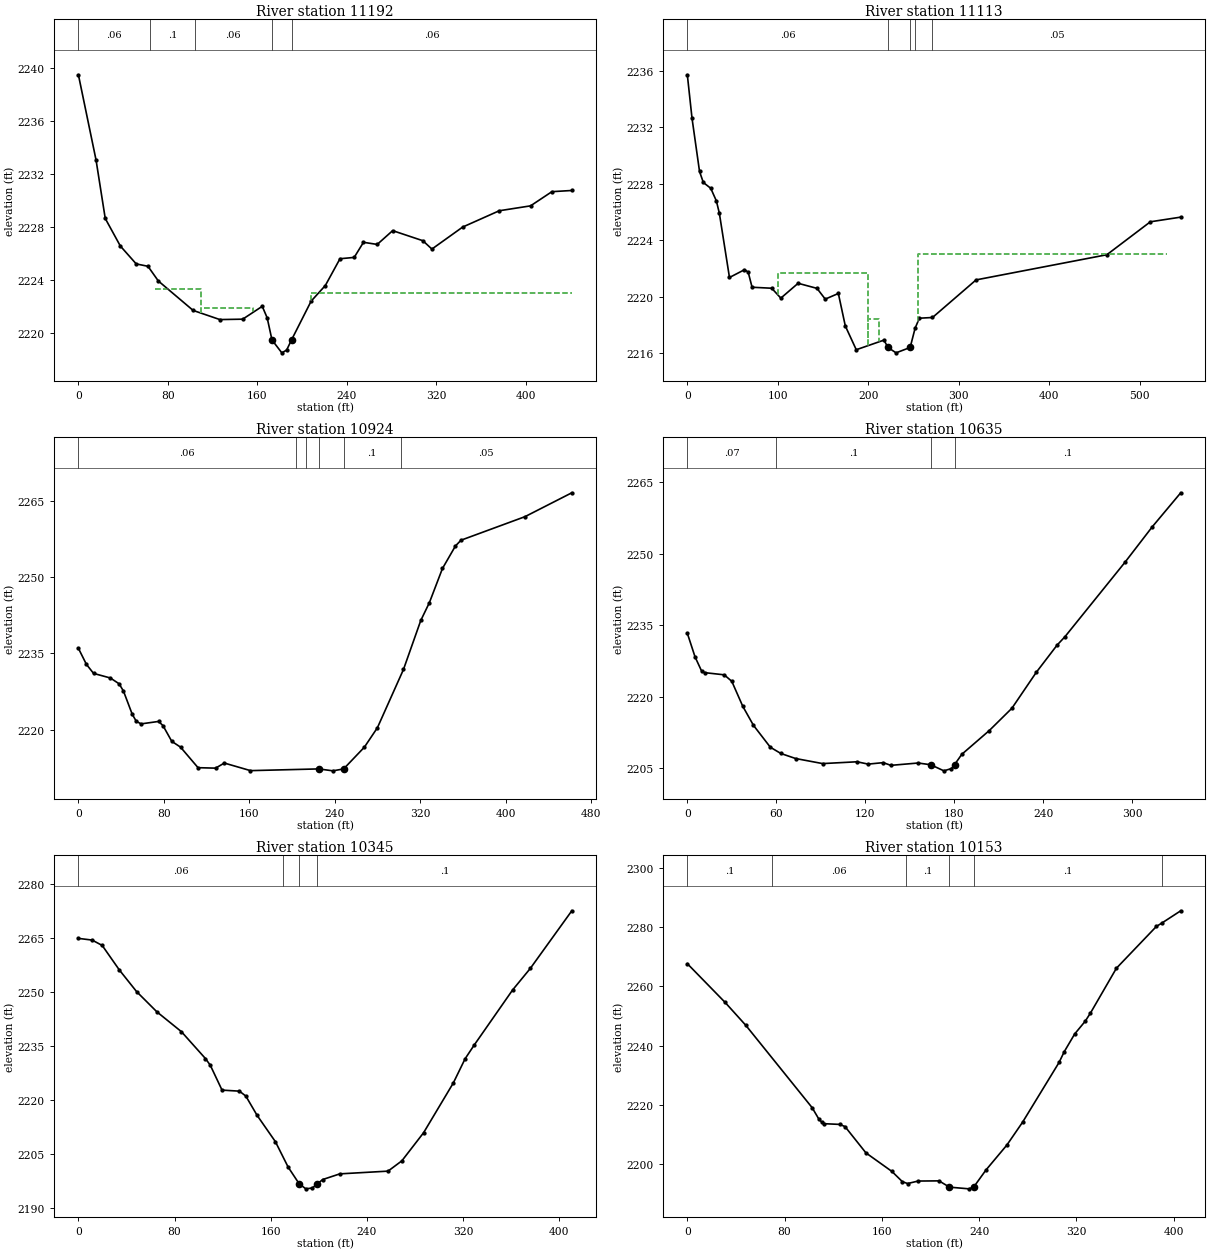
Type RM Length L Ch R = 1 ,11192   ,79.4,78.3,78.8
BEGIN DESCRIPTION:
Structure XS 3; 17.7 ft between structure
END DESCRIPTION:
XS GIS Cut Line= 6
2207111.74196285424010.390705673 2207088.1069678424006.026507543
2207025.93549481424068.9044745372206974.74723332424195.484558888
2206960.93804579424261.0708455752206954.27355231424385.995051488
#Sta/Elev= 30
       0 2239.48    15.8 2233.04      24 2228.64    37.5 2226.56    51.7 2225.21
    62.2 2225.03    71.5 2223.92   102.6  2221.7   126.5 2221.01   146.9 2221.04
   164.4 2222.01   168.8 2221.14   173.1 2219.47   181.9  2218.5   186.2 2218.71
   190.6 2219.48   208.1  2222.4   220.8 2223.58   233.9  2225.6   246.6  2225.7
   254.9 2226.84   267.2 2226.68     281 2227.72     308 2226.96   316.1 2226.33
   343.6 2227.99   376.3 2229.22   404.3 2229.59   423.4 2230.66   441.2 2230.75
#Mann= 5 ,-1,0
       0     .06       0   64.03      .1       0  104.03     .06       0
   173.1    .045       0   190.6     .06       0
#XS Ineff= 4 ,-1
       0   68.69  2221.9   68.69  109.79 2223.32  109.79     156  2221.9
     208   441.2    2223
Permanent Ineff=
       F       F       F       F
Bank Sta=173.1,190.6
XS Rating Curve= 0 ,0
Exp/Cntr(USF)=0,0
Exp/Cntr=0.5,0.3

Type RM Length L Ch R = 1 ,11113   ,157,189.3,207.2
BEGIN DESCRIPTION:
Structure XS 2; 27.3 ft between structure and xs
END DESCRIPTION:
XS GIS Cut Line= 6
 2207109.2366795423995.4366750862207040.06537504423977.060253085
2206950.87922422424061.4002251032206917.61803722424127.263635111
2206936.91724941424172.0526001672206929.16046059424390.822853214
#Sta/Elev= 30
       0  2235.7     5.2 2232.62    13.5 2228.86    17.7 2228.08    25.9 2227.67
    32.1 2226.78    35.4 2225.91    46.6 2221.36    63.2 2221.91    67.3 2221.74
    71.6 2220.67    93.3  2220.6   103.4  2219.9   122.5 2220.95   143.4 2220.59
   152.5 2219.83     167 2220.23   174.7 2217.93   186.8 2216.25   217.4 2216.93
   221.9 2216.41   230.8 2216.03   246.4 2216.41   251.9 2217.78   256.6 2218.48
   271.1 2218.53   319.3 2221.19   463.9 2222.97     512  2225.3   545.6 2225.63
#Mann= 5 ,-1,0
       0     .06       0   221.9    .045       0   246.4     .06       0
   251.9      .1       0   271.1     .05       0
#XS Ineff= 3 ,-1
   100.3  200.02 2221.66  200.02     212  2218.4     255   530.8    2223
Permanent Ineff=
       F       F       F
Bank Sta=221.9,246.4
XS Rating Curve= 0 ,0
Exp/Cntr(USF)=0,0
Exp/Cntr=0.5,0.3

Type RM Length L Ch R = 1 ,10924   ,272,288.8,292.9
BEGIN DESCRIPTION:
Structure XS 1
END DESCRIPTION:
XS GIS Cut Line= 4
2207133.32258451423977.0602530852207042.41585587423956.038386678
2206878.16841453423919.3350478322206680.98787495423884.047708874
#Sta/Elev= 30
       0 2236.01     7.5 2232.86    14.2 2231.08    29.9 2230.18    38.1 2229.04
    42.2  2227.6    50.4 2223.05    54.2 2221.66    58.7 2221.16    75.1 2221.64
    79.2 2220.81    87.4 2217.73    95.6 2216.59     112 2212.55   128.4 2212.46
   136.6 2213.46   161.1 2211.97  224.922212.308   238.3 2211.93   248.3 2212.31
   267.7 2216.58   279.9  2220.4   304.3 2231.85   320.5 2241.48   328.6    2245
   340.8  2251.7     353 2256.14   358.2 2257.26     418 2261.88   461.9 2266.58
#Mann= 6 ,-1,0
       0     .06       0  203.31     .05       0  213.31      .1       0
  224.92    .045       0   248.3      .1       0   301.6     .05       0
Bank Sta=224.92,248.3
XS Rating Curve= 0 ,0
Exp/Cntr(USF)=0,0
Exp/Cntr=0.3,0.1

Type RM Length L Ch R = 1 ,10635   ,293.9,289.7,287.1
XS GIS Cut Line= 2
2207171.42786554423912.6607153292206964.28359829423651.994460136
#Sta/Elev= 30
       0 2233.29     5.2 2228.34     9.6 2225.38    11.7 2225.03    24.9 2224.57
      30 2223.21    37.4 2217.98    44.6 2213.99      56 2209.39    63.1 2208.08
    73.1 2207.02    91.3 2205.96   114.5 2206.34     122 2205.85   132.2 2206.16
   137.3 2205.59   155.7 2206.08   164.2 2205.72   173.1 2204.44   178.2 2204.92
  180.312205.754   185.2 2207.91   203.7 2212.88     219 2217.57   235.4 2225.08
   249.5 2230.81   254.8 2232.57   295.2 2248.14   313.8 2255.65   332.9 2262.74
#Mann= 4 ,-1,0
       0     .07       0      60      .1       0   164.2    .045       0
  180.31      .1       0
Bank Sta=164.2,180.31
XS Rating Curve= 0 ,0
Exp/Cntr(USF)=0,0
Exp/Cntr=0.3,0.1

Type RM Length L Ch R = 1 ,10345   ,196.1,193,190.1
XS GIS Cut Line= 2
2207469.14411621423775.8203071282207136.18529928 423535.78672209
#Sta/Elev= 30
       0 2264.95    11.4 2264.48    19.8 2262.99    34.1 2256.16    48.4 2250.17
    65.3 2244.54    85.7 2239.03   105.7 2231.56   109.7 2229.72   119.5 2222.79
     134  2222.5   139.3 2221.13   148.7 2215.76   163.9 2208.46   174.5  2201.4
   183.6  2196.8   189.2 2195.36   194.6  2195.6   198.4 2196.62   203.2 2197.94
   217.5 2199.52   257.6 2200.28   269.1 2203.14   287.2 2210.96   311.9 2224.77
   321.7 2231.49   329.2 2235.27   361.2  2250.6     376 2256.62   410.5 2272.62
#Mann= 4 ,-1,0
       0     .06       0     170      .1       0   183.6    .045       0
   198.4      .1       0
Bank Sta=183.6,198.4
XS Rating Curve= 0 ,0
Exp/Cntr(USF)=0,0
Exp/Cntr=0.3,0.1

Type RM Length L Ch R = 1 ,10153   ,196.4,196.8,197.1
XS GIS Cut Line= 2
2207589.01329773 423565.314314882207210.93638586423417.905494042
#Sta/Elev= 30
       0 2267.65      31 2254.62    48.1 2246.85   102.7 2219.04   108.2 2215.19
   110.5 2214.21   112.5 2213.66   125.4 2213.42   129.7 2212.68   146.9 2203.81
   168.3 2197.54   176.9 2194.08   181.2 2193.47   189.8 2194.31     207 2194.37
   215.6 2192.25   231.6 2191.68   235.5 2192.27   245.6 2198.03   262.8 2206.45
   275.7 2214.15   305.7 2234.31     310 2237.96   318.6 2243.95   327.2 2248.22
   331.5 2250.96   352.9 2266.12   385.8 2280.23     390 2281.29   405.8  2285.5
#Mann= 6 ,-1,0
       0      .1       0      70     .06       0     180      .1       0
   215.6    .045       0   235.5      .1       0     390     .05       0
Bank Sta=215.6,235.5
XS Rating Curve= 0 ,0
Exp/Cntr(USF)=0,0
Exp/Cntr=0.3,0.1

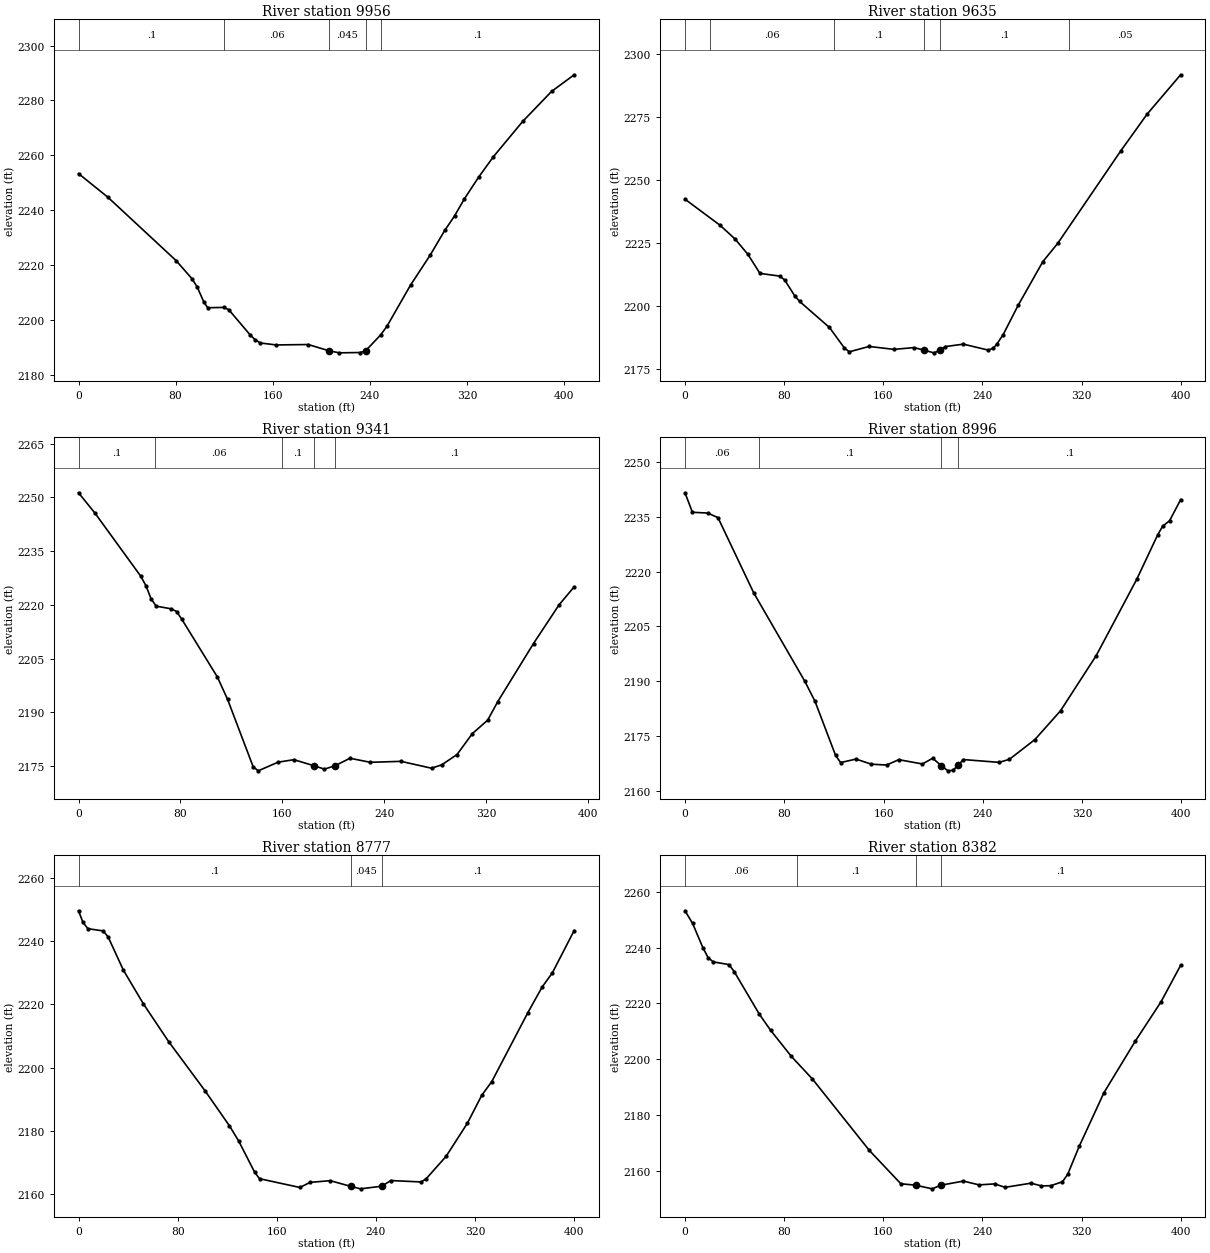
Type RM Length L Ch R = 1 ,9956    ,322.8,320.7,307.7
XS GIS Cut Line= 3
2207654.41682878423386.2401970012207424.79587324423290.202041917
2207265.97639806423275.048537406
#Sta/Elev= 30
       0 2253.31    24.1 2244.72    80.5 2221.53    93.5 2214.94    97.8 2211.94
   103.4 2206.33   106.5 2204.37   119.5 2204.49   123.8 2203.66   141.2 2194.57
   145.5  2192.7   149.8 2191.52   162.9  2190.8   189.3 2190.95   206.2  2188.7
   214.9 2187.92   232.2 2188.04   236.6 2188.69   248.9 2194.43   254.1 2197.58
   273.6 2212.65   289.7 2223.51   301.8 2232.61   309.8 2237.83   317.8 2243.99
   329.9 2252.15   341.9 2259.49     366 2272.34   389.8 2283.28   408.4 2289.35
#Mann= 5 ,-1,0
       0      .1       0     120     .06       0   206.2    .045       0
   236.6     .06       0   248.9      .1       0
Bank Sta=206.2,236.6
XS Rating Curve= 0 ,0
Exp/Cntr(USF)=0,0
Exp/Cntr=0.3,0.1

Type RM Length L Ch R = 1 ,9635    ,293.9,293.8,292.7
XS GIS Cut Line= 2
2207640.54340649 423018.396577172207241.19807464422995.520696213
#Sta/Elev= 30
       0 2242.38    28.4 2231.97    40.4 2226.55    50.8 2220.43    60.5 2212.86
    76.5 2211.79    80.5 2210.23    88.5 2203.99    92.5 2201.72   116.6 2191.35
   128.6 2183.23   132.6 2181.68   148.6 2183.81   168.6 2182.65   184.7 2183.35
   192.7 2182.39   200.7 2181.27   206.1 2182.25   209.9 2183.75   224.7 2184.72
   244.8 2182.35   248.8 2183.11   251.6 2184.68   256.8 2188.53   268.8  2200.1
   288.8 2217.54   300.9 2224.87   351.8 2261.68     373 2276.24     400 2291.86
#Mann= 6 ,-1,0
       0      .1       0      20     .06       0     120      .1       0
   192.7    .045       0   206.1      .1       0     310     .05       0
Bank Sta=192.7,206.1
XS Rating Curve= 0 ,0
Exp/Cntr(USF)=0,0
Exp/Cntr=0.3,0.1

Type RM Length L Ch R = 1 ,9341    ,347.9,345.5,340.1
XS GIS Cut Line= 2
2207681.10545787422724.6852373012207292.29961744422716.795433241
#Sta/Elev= 30
       0 2251.27    12.9  2245.6    48.9 2227.96    52.9 2225.34    56.9 2221.72
    60.9 2219.64    72.9 2218.88    76.9 2218.14    80.9 2216.06     109 2199.84
     117 2193.59     137 2174.85     141 2173.68   156.6  2176.1     169 2176.79
   184.7 2175.11     193 2174.15   201.6 2175.16     213 2177.19     229 2176.06
     253 2176.33     277 2174.41     285 2175.36     297 2178.23     309 2184.06
     321 2187.81     329 2193.02     357 2209.21     377 2219.98   388.9 2225.03
#Mann= 5 ,-1,0
       0      .1       0      60     .06       0     160      .1       0
   184.7    .045       0   201.6      .1       0
Bank Sta=184.7,201.6
XS Rating Curve= 0 ,0
Exp/Cntr(USF)=0,0
Exp/Cntr=0.3,0.1

Type RM Length L Ch R = 1 ,8996    ,212.6,218.6,224.8
XS GIS Cut Line= 2
2207585.98937897422370.5713226252207198.11557385422465.892990822
#Sta/Elev= 30
       0 2241.61       6 2236.27    18.3 2236.06    26.6  2234.8    55.4  2214.2
    96.6 2189.98   104.8 2184.48   121.3 2169.75   125.4 2167.73   137.8 2168.69
   150.2 2167.29   162.5 2167.06   172.3 2168.53   191.3 2167.35   199.6 2168.91
   206.4 2166.93   211.9 2165.47   216.1 2165.63  220.042167.006   224.3 2168.56
   253.1 2167.79   261.4 2168.62     282 2174.04   302.6 2181.91   331.4 2197.04
   364.1 2217.96   380.8 2230.02   384.9 2232.45   390.5 2233.96   399.4 2239.72
#Mann= 4 ,-1,0
       0     .06       0      60      .1       0   206.4    .045       0
  220.04      .1       0
Bank Sta=206.4,220.04
XS Rating Curve= 0 ,0
Exp/Cntr(USF)=0,0
Exp/Cntr=0.3,0.1

Type RM Length L Ch R = 1 ,8777    ,391.9,395.4,397.8
XS GIS Cut Line= 2
2207607.67899342422253.0423631892207214.87188077422177.526985617
#Sta/Elev= 30
       0 2249.69     3.6 2245.99     7.6 2244.02    19.9 2243.31    23.9  2241.4
    36.2 2230.89    52.4 2220.17    72.8 2208.21     102 2192.72   121.7 2181.62
   129.3 2176.72   142.1 2166.88   146.1  2164.8   178.7 2162.02   186.9 2163.64
   203.2 2164.18   219.5 2162.39   227.6 2161.59  244.77 2162.43     252 2164.22
   276.5 2163.77   280.5 2164.76   296.7 2171.91   313.8 2182.36   325.4 2191.21
   333.5 2195.57   362.6 2217.39   374.2 2225.56   382.4 2230.03     400 2243.43
#Mann= 3 ,0,0
       0      .1       0   219.5    .045       0  244.77      .1       0
Bank Sta=219.5,244.77
XS Rating Curve= 0 ,0
Exp/Cntr(USF)=0,0
Exp/Cntr=0.3,0.1

Type RM Length L Ch R = 1 ,8382    ,320.4,319.1,317.4
XS GIS Cut Line= 2
2207709.95037676421911.1388035942207329.36056369 421788.04780396
#Sta/Elev= 30
       0 2253.18     6.1  2248.7    14.5 2239.92    18.7 2236.37    22.9 2234.86
    35.5  2233.9    39.7  2231.4    60.1 2216.06    69.1 2210.37    85.9 2200.98
   102.8 2192.94   148.8 2167.32   174.2 2155.38   186.1 2154.87   199.5 2153.56
   206.3 2154.84   224.7 2156.34   237.3 2154.98   249.9 2155.33   258.3  2154.1
   279.3 2155.59   287.7  2154.6   295.2 2154.69   304.6 2156.09   308.8  2158.7
   318.3 2168.94   338.2 2188.07   363.4 2206.47   384.2 2220.59     400 2233.63
#Mann= 4 ,-1,0
       0     .06       0      90      .1       0   186.1    .045       0
   206.3      .1       0
Bank Sta=186.1,206.3
XS Rating Curve= 0 ,0
Exp/Cntr(USF)=0,0
Exp/Cntr=0.3,0.1

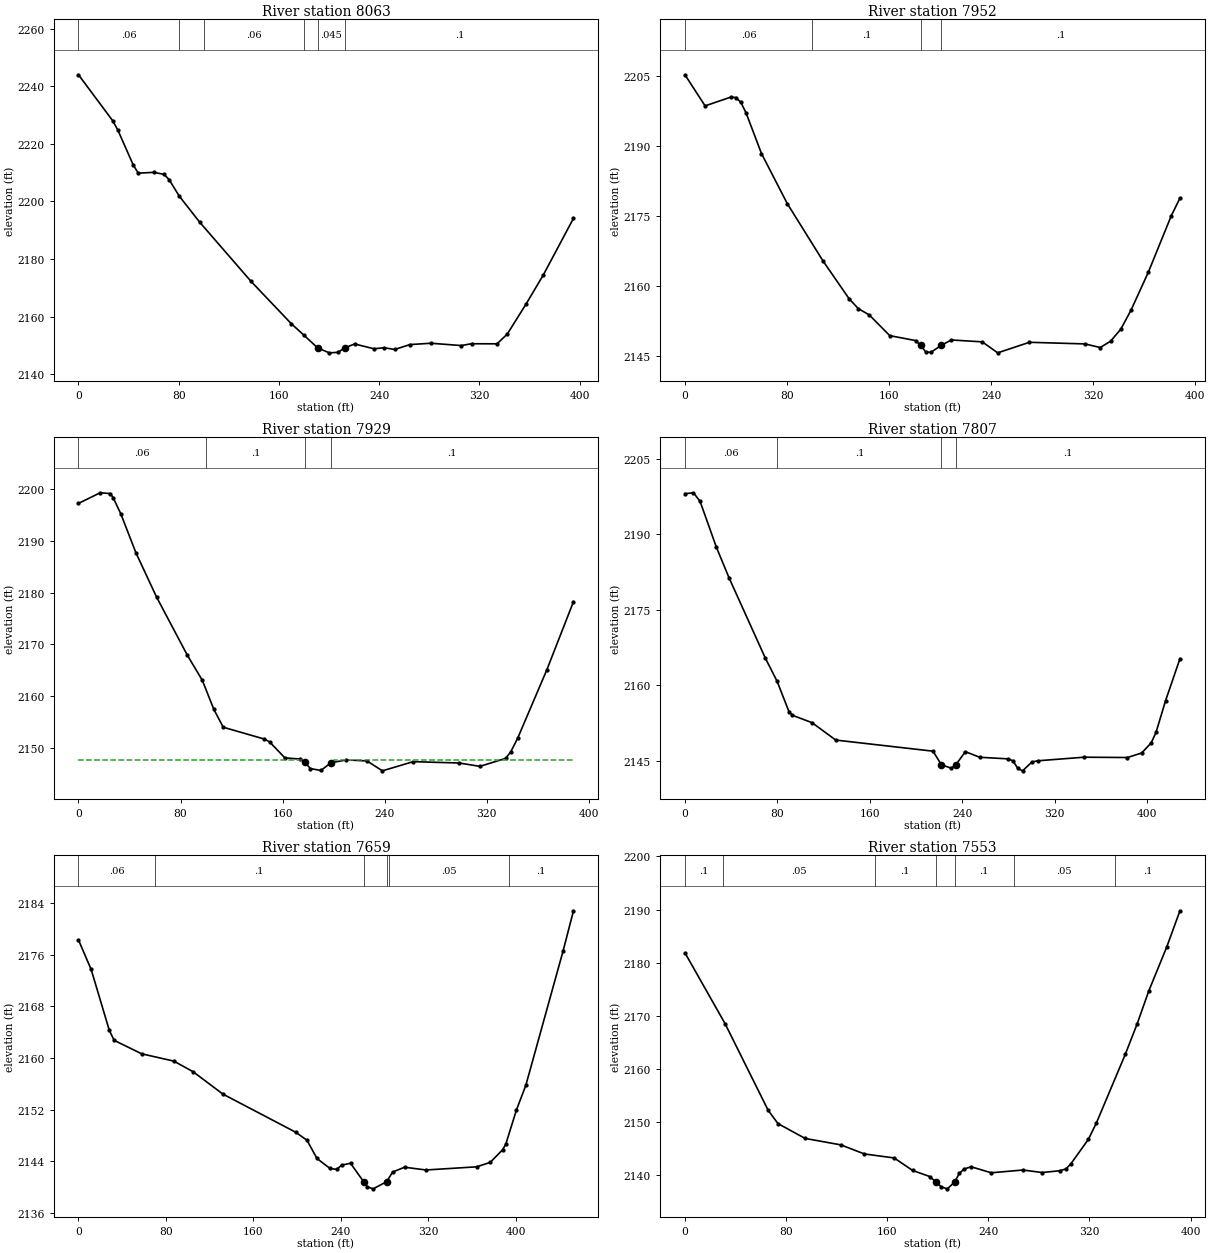
Type RM Length L Ch R = 1 ,8063    ,111.7,110.4,109.1
BEGIN DESCRIPTION:
Structure XS 4
END DESCRIPTION:
XS GIS Cut Line= 2
2207802.80176141421588.4718778372207416.62103282421505.211943052
#Sta/Elev= 30
       0 2243.96    27.2 2228.07    31.3 2224.88    43.6 2212.75    47.7 2209.81
      60 2210.08    68.2 2209.41    72.3  2207.6    80.4 2201.86    96.8 2192.76
   137.7 2172.25   169.9 2157.53     180 2153.53   190.9 2149.14   200.2 2147.43
     207  2147.6     213 2149.23   220.4 2150.51   235.9 2148.84   244.1 2149.21
   252.3 2148.59   264.6  2150.3   281.3 2150.76   305.5 2149.96   313.7 2150.59
   334.1 2150.56   342.3 2153.97   357.3 2164.41     371 2174.45   395.1 2194.12
#Mann= 6 ,-1,0
       0     .06       0      80      .1       0     100     .06       0
     180      .1       0   190.9    .045       0     213      .1       0
Bank Sta=190.9,213
XS Rating Curve= 0 ,0
Exp/Cntr(USF)=0,0
Exp/Cntr=0.5,0.3

Type RM Length L Ch R = 1 ,7952    ,23,22.9,23
BEGIN DESCRIPTION:
Structure XS 3; 9.4 ft between structure and xs
END DESCRIPTION:
XS GIS Cut Line= 2
 2207819.8597911421459.465014881  2207434.114061421417.075374211
#Sta/Elev= 30
       0 2205.24    15.8 2198.58    35.9 2200.45    39.9 2200.37    43.9 2199.31
      48 2197.02      60 2188.37    80.2 2177.66   108.3 2165.34   128.7 2157.27
   135.9 2155.16   144.5  2153.8   160.6 2149.36   180.8 2148.31   184.8 2147.29
   188.8 2145.87   192.8 2145.77   200.9 2147.29   208.9 2148.44   233.1 2148.03
   245.2 2145.68   270.1 2147.94   313.6 2147.59   325.6 2146.82   333.7 2148.17
   341.7 2150.74   349.7  2154.8   363.3 2162.95   381.3 2175.04   388.1 2178.82
#Mann= 4 ,-1,0
       0     .06       0     100      .1       0   184.8    .045       0
   200.9      .1       0
#XS Ineff= 2 , 0
             175  2147.7     210          2147.6
Permanent Ineff=
       F       F
Bank Sta=184.8,200.9
XS Rating Curve= 0 ,0
Exp/Cntr(USF)=0,0
Exp/Cntr=0.5,0.3

Type RM Length L Ch R = 1 ,7929    ,124.5,122.5,121
BEGIN DESCRIPTION:
Structure XS 2; 7.6 ft between structure and xs
END DESCRIPTION:
XS GIS Cut Line= 2
2207817.03381505421436.1507125122207431.28808496421393.761071842
#Sta/Elev= 30
       0 2197.19      17 2199.24      25 2199.09    27.2 2198.28    33.1 2195.23
    45.1 2187.63    61.2 2179.14    85.4 2167.89    97.1 2163.07   106.1 2157.48
   113.5 2154.02   145.7 2151.74   149.8  2151.2   161.8 2148.12   173.9 2147.87
   177.5 2147.23   181.9 2146.05     190 2145.68     198 2147.17   210.1 2147.72
   226.2 2147.52   238.3 2145.61   262.4 2147.38   298.6 2147.12   314.7 2146.47
   334.9 2148.01   338.9 2149.26   344.3 2151.88   367.1 2165.03   388.1 2178.24
#Mann= 4 ,-1,0
       0     .06       0     100      .1       0   177.5    .045       0
     198      .1       0
#XS Ineff= 2 , 0
             175  2147.7   200.5          2147.7
Permanent Ineff=
       F       F
Bank Sta=177.5,198
XS Rating Curve= 0 ,0
Exp/Cntr(USF)=0,0
Exp/Cntr=0.5,0.3

Type RM Length L Ch R = 1 ,7807    ,152.2,147.8,143.9
BEGIN DESCRIPTION:
Structure XS 1
END DESCRIPTION:
XS GIS Cut Line= 4
 2207815.1016599421420.5927869382207651.42519895421293.056760508
2207613.89522297421293.0567605082207436.08962234421337.822536752
#Sta/Elev= 30
       0 2198.09     7.4 2198.27    13.1 2196.55    27.3 2187.39    38.1 2181.39
    69.6 2165.37    79.8 2160.76      90 2154.75    92.9 2154.03     110 2152.55
   130.5 2149.09   214.7 2146.88  221.942144.179   230.6 2143.49   234.6 2144.23
   242.7 2146.78   255.1 2145.67   279.8 2145.35   283.9 2144.96   288.1 2143.44
   292.2 2142.97   300.4 2144.75   305.9 2144.98   345.4 2145.68   382.9 2145.62
   395.3 2146.52   403.5 2148.53   407.7 2150.62   415.9 2156.89   428.4 2165.27
#Mann= 4 ,-1,0
       0     .06       0      80      .1       0  221.94    .045       0
   234.6      .1       0
Bank Sta=221.94,234.6
XS Rating Curve= 0 ,0
Exp/Cntr(USF)=0,0
Exp/Cntr=0.3,0.1

Type RM Length L Ch R = 1 ,7659    ,107.4,106.1,104.2
XS GIS Cut Line= 3
2207783.24802499421129.5779669412207694.14851359421101.130532577
2207376.93278323421269.668162583
#Sta/Elev= 30
       0 2178.27    11.6  2173.7    28.2 2164.27    32.6 2162.73    57.8 2160.64
    87.2 2159.51   104.8 2157.87     132 2154.41   198.6  2148.5     209 2147.25
   218.1 2144.43     230 2142.89   236.2 2142.74   240.7 2143.41   248.8 2143.69
   260.7 2140.86   264.1 2140.04   269.5 2139.73   281.8 2140.83   287.3 2142.33
   298.2 2143.08   317.7 2142.65   364.2 2143.14   376.6 2143.83   387.9 2145.79
   390.8 2146.65   400.5 2151.93   409.1 2155.75   443.2 2176.57   452.7 2182.79
#Mann= 6 ,-1,0
       0     .06       0      70      .1       0   260.7    .045       0
   281.8      .1       0  283.53     .05       0  393.53      .1       0
Bank Sta=260.7,281.8
XS Rating Curve= 0 ,0
Exp/Cntr(USF)=0,0
Exp/Cntr=0.3,0.1

Type RM Length L Ch R = 1 ,7553    ,84.5,84.5,84.1
BEGIN DESCRIPTION:
Structure XS 4
END DESCRIPTION:
XS GIS Cut Line= 2
2207645.35577034420998.8309195982207311.18410306421203.007688826
#Sta/Elev= 30
       0 2181.86    31.7 2168.56    65.9 2152.21    73.6 2149.74    95.1 2146.95
   123.3 2145.74     142 2144.03   165.5 2143.28   180.1 2140.93   193.6 2139.79
   198.3 2138.82   202.9 2137.82   207.6 2137.47   213.4 2138.76     217 2140.36
   220.8  2141.2   226.4 2141.62   242.3 2140.49   267.4 2141.01   282.6 2140.54
   296.7 2140.88   301.4 2141.22   305.2 2142.14   319.1 2146.76   325.5 2149.86
   348.3 2162.74   357.6 2168.41     367 2174.73   381.1 2182.93   391.6 2189.77
#Mann= 7 ,-1,0
       0      .1       0      30     .05       0     150      .1       0
   198.3    .045       0   213.4      .1       0     260     .05       0
     340      .1       0
Bank Sta=198.3,213.4
XS Rating Curve= 0 ,0
Exp/Cntr(USF)=0,0
Exp/Cntr=0.5,0.3