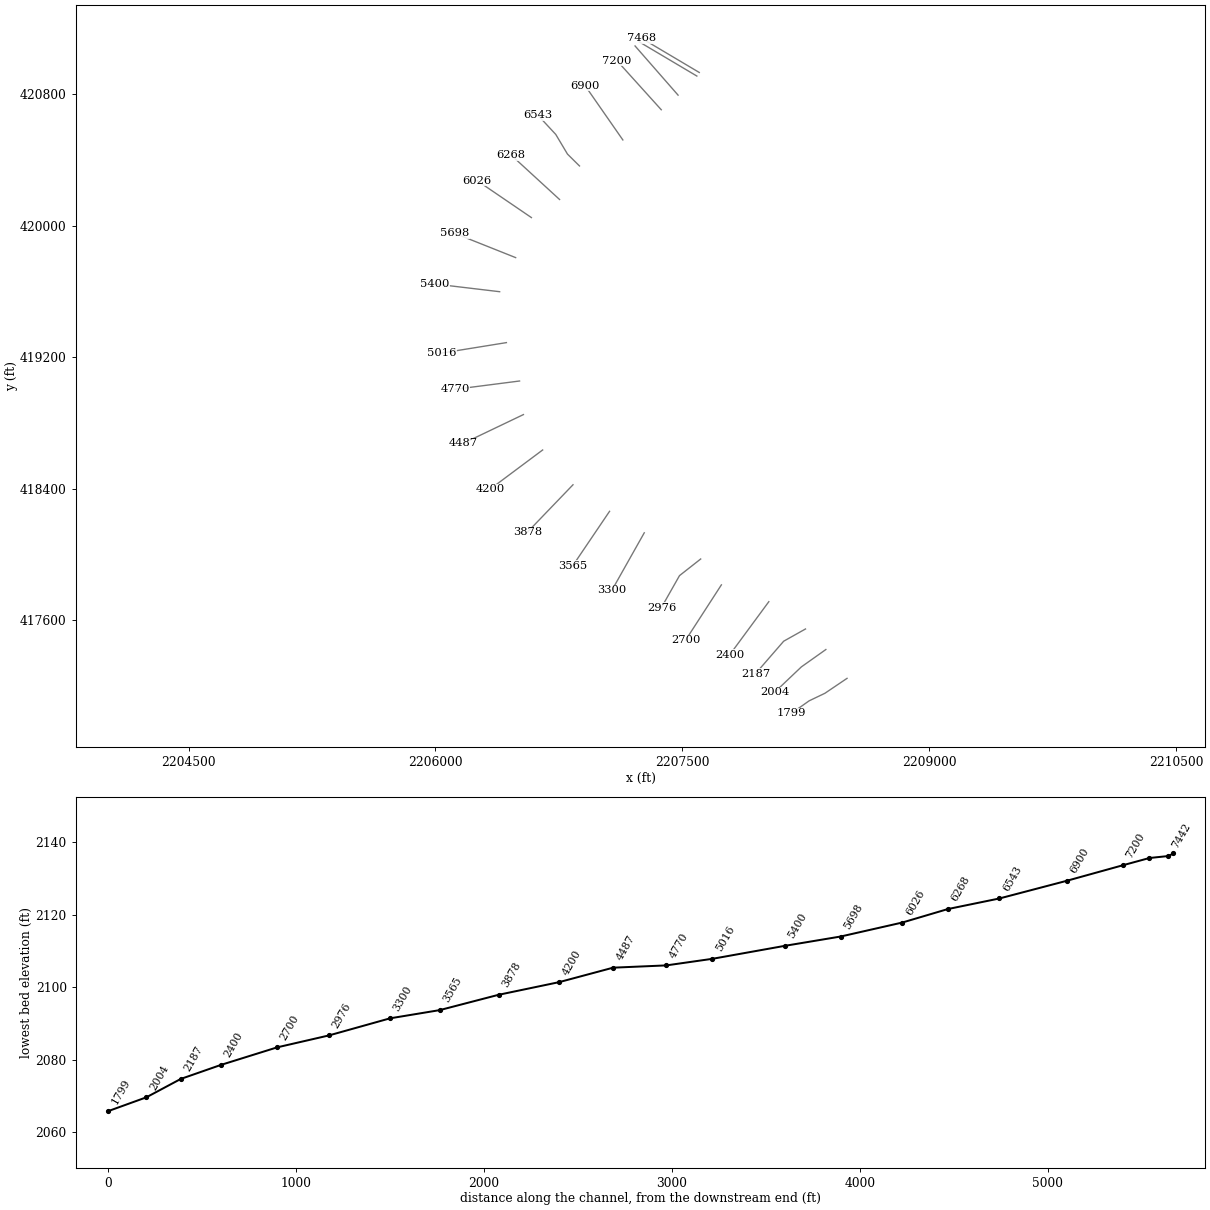
HEC-RAS study STVNSHLRN.prj: STVNSHLRN

--- STVNSHLRN.g01 (geometry) --- (continued)

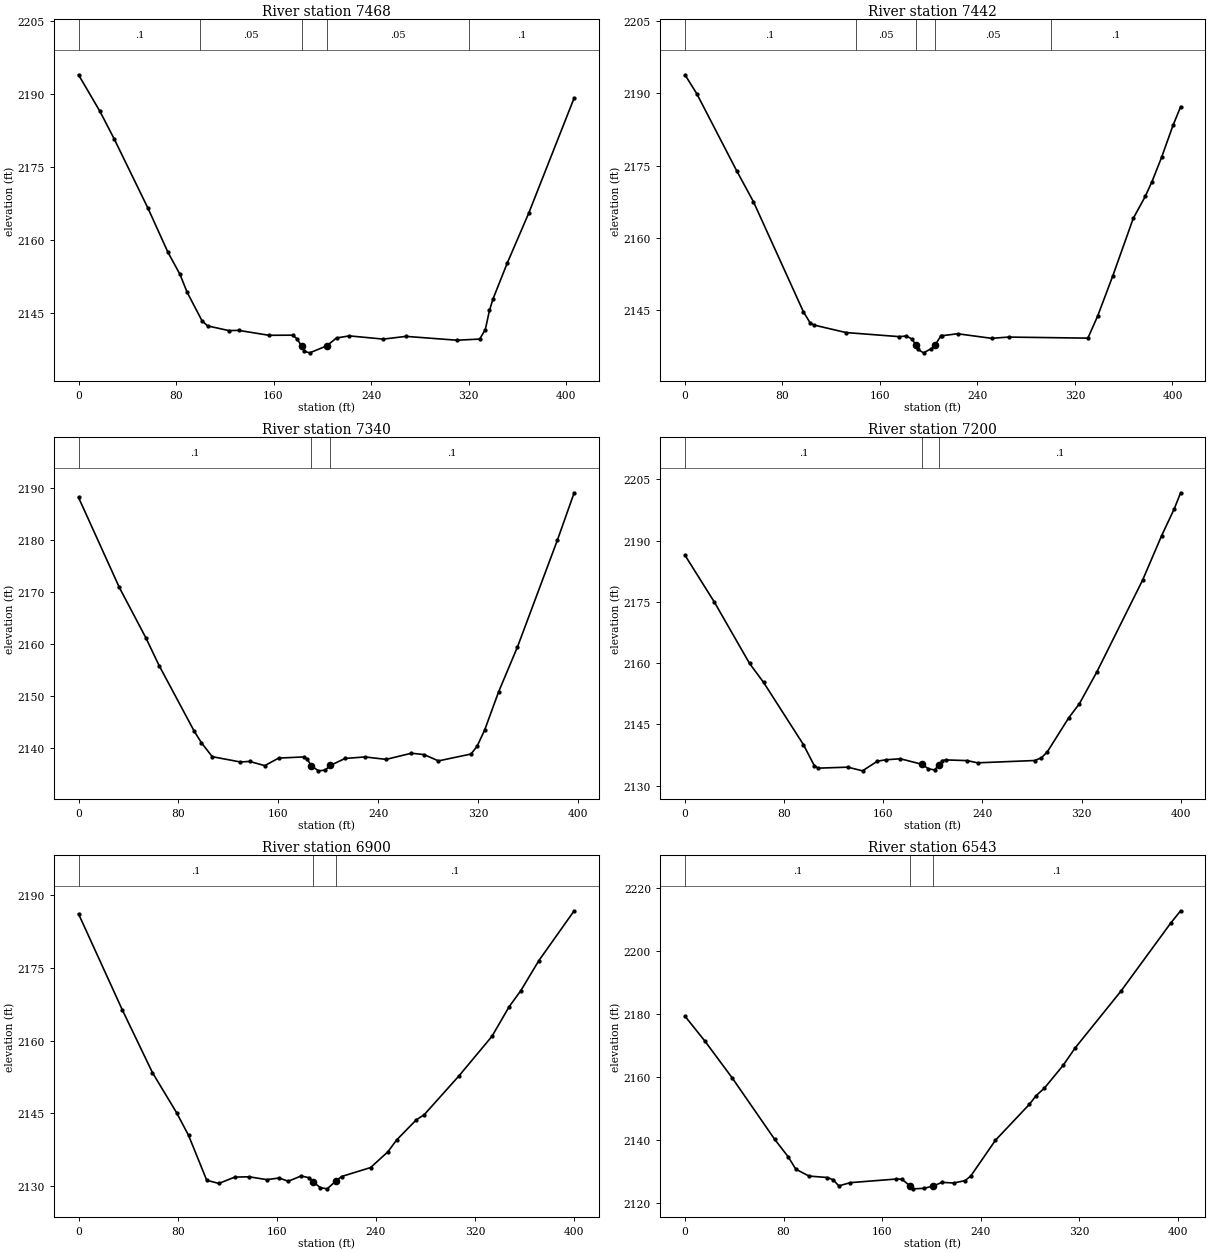
Type RM Length L Ch R = 1 ,7468    ,27.4,26.6,26.4
BEGIN DESCRIPTION:
Structure XS 3; 11.8 ft between structure and xs
END DESCRIPTION:
XS GIS Cut Line= 2
2207603.29464355420930.1872304412207253.47928031421137.692790364
#Sta/Elev= 30
       0 2193.98    17.6 2186.46    29.4 2180.75      57 2166.58    73.4 2157.53
    83.3 2152.98    89.1 2149.34   101.3 2143.49   105.9 2142.42   123.5 2141.45
   131.3 2141.51   156.3 2140.49   175.7 2140.52   179.6 2139.71  182.982138.231
   185.4 2137.18   189.7 2136.89   203.6 2138.31   211.7 2139.94   222.2 2140.37
   250.1 2139.71   268.7 2140.27   310.6 2139.48   329.2 2139.72   333.8 2141.68
   337.2  2145.6   340.2 2148.02   351.8 2155.32   369.4 2165.56   406.7 2189.23
#Mann= 5 ,-1,0
       0      .1       0     100     .05       0  182.98    .045       0
   203.6     .05       0     320      .1       0
#XS Ineff= 2 , 0
             171  2138.2     215          2138.9
Permanent Ineff=
       F       F
Bank Sta=182.98,203.6
XS Rating Curve= 0 ,0
Exp/Cntr(USF)=0,0
Exp/Cntr=0.5,0.3

Type RM Length L Ch R = 1 ,7442    ,105.1,101.3,96.9
BEGIN DESCRIPTION:
Structure XS 2; 12.9 ft between structure and xs
END DESCRIPTION:
XS GIS Cut Line= 2
 2207588.5334163420908.5015258492207238.71805306421116.007085772
#Sta/Elev= 30
       0 2193.86     9.7 2189.92    42.3    2174    56.2 2167.51    97.1 2144.73
   102.7 2142.38   105.8 2141.94   132.1 2140.38   175.9 2139.53   181.7 2139.67
   186.4 2139.01   189.5 2137.73   191.1 2136.87   195.8 2136.17   202.2 2137.06
   205.2 2137.79   209.7 2139.56   210.9 2139.72   223.7 2140.13   251.6 2139.18
   265.5 2139.44   330.6 2139.22   338.5 2143.73   351.1 2152.18   367.8 2164.05
   377.7 2168.64   383.2  2171.7   391.1 2176.74   400.4 2183.34   406.7 2187.23
#Mann= 5 ,-1,0
       0      .1       0     140     .05       0   189.5    .045       0
   205.2     .05       0     300      .1       0
#XS Ineff= 2 , 0
             184  2138.2     210          2138.9
Permanent Ineff=
       F       F
Bank Sta=189.5,205.2
XS Rating Curve= 0 ,0
Exp/Cntr(USF)=0,0
Exp/Cntr=0.5,0.3

Type RM Length L Ch R = 1 ,7340    ,140.1,140.6,140.5
BEGIN DESCRIPTION:
Structure XS 1
END DESCRIPTION:
XS GIS Cut Line= 2
2207474.38421964420792.5346683372207212.98143551421091.381635062
#Sta/Elev= 30
       0 2188.11    32.7 2170.82      54 2161.13    64.6 2155.81    92.7 2143.22
    98.4 2141.03   107.1 2138.34   129.6 2137.32     137 2137.43   149.2 2136.62
   160.3 2138.07   180.6 2138.29   183.4 2137.83   186.3 2136.62   192.2 2135.62
   197.6 2135.76  201.65 2136.65   213.4 2137.99   229.4 2138.29   246.4 2137.82
   266.6    2139   276.8 2138.74   288.3 2137.53   314.4 2138.85   319.3 2140.36
   325.4 2143.51   336.5  2150.8   351.6 2159.41   383.5 2179.87     397    2189
#Mann= 3 ,-1,0
       0      .1       0   186.3    .045       0  201.65      .1       0
Bank Sta=186.3,201.65
XS Rating Curve= 0 ,0
Exp/Cntr(USF)=0,0
Exp/Cntr=0.3,0.1

Type RM Length L Ch R = 1 ,7200    ,297.3,300,296.1
XS GIS Cut Line= 2
2207372.24040131420703.6880187342207104.13344089421000.535888484
#Sta/Elev= 30
       0 2186.42    23.8  2174.9    52.1 2159.93    63.4  2155.3    95.6 2140.04
   104.4 2134.88   107.5 2134.29   131.4 2134.53   143.3 2133.63   155.3    2136
   162.5 2136.35   173.9 2136.58   191.1 2135.24   196.5 2134.14   201.4 2133.85
     205 2135.11   207.8 2136.16   210.7  2136.3   227.7 2136.14   236.2 2135.59
   282.3 2136.16   287.7 2136.83   292.5 2138.32   309.8 2146.66   318.3 2150.06
   332.5 2157.92   369.3 2180.32   384.7 2191.23   394.8 2197.75     400 2201.71
#Mann= 3 ,-1,0
       0      .1       0   191.1    .045       0     205      .1       0
Bank Sta=191.1,205
XS Rating Curve= 0 ,0
Exp/Cntr(USF)=0,0
Exp/Cntr=0.3,0.1

Type RM Length L Ch R = 1 ,6900    ,353,357.2,353
XS GIS Cut Line= 2
 2207138.7704162420520.2110360672206910.31219096420848.550554432
#Sta/Elev= 30
       0  2186.2    35.3 2166.36    59.7 2153.34    79.1 2145.09    88.8 2140.38
   103.5 2131.08   113.3 2130.44   126.1 2131.75   137.7 2131.81     152 2131.22
     162 2131.57   169.2 2130.88   179.6 2131.98   186.4  2131.6   189.3 2130.79
   195.1 2129.57   200.6 2129.32   207.6 2130.89   212.3 2131.87   235.7 2133.72
   249.7 2136.99   256.7 2139.42   272.7 2143.62   278.9 2144.63   307.2 2152.73
   333.7 2160.88   347.4 2166.94   356.9  2170.3   371.5 2176.52     400 2186.83
#Mann= 3 ,-1,0
       0      .1       0   189.3    .045       0   207.6      .1       0
Bank Sta=189.3,207.6
XS Rating Curve= 0 ,0
Exp/Cntr(USF)=0,0
Exp/Cntr=0.3,0.1

Type RM Length L Ch R = 1 ,6543    ,268.3,275,277.7
XS GIS Cut Line= 4
2206875.31715893420361.9893038672206802.34769076420434.073887286
2206731.17449783420553.5139581782206621.95734485420671.046616772
#Sta/Elev= 30
       0  2179.2    15.9 2171.44    38.2 2159.69    72.8 2140.14    83.7 2134.63
    89.9  2130.7   100.6 2128.51   115.5 2128.05   120.2 2127.33   124.8  2125.4
   134.1 2126.42   171.4 2127.57     176 2127.51   182.3 2125.46   185.3 2124.46
     194 2124.62201.58882125.389   208.5 2126.52   217.9 2126.31   227.2 2127.06
   231.9 2128.56   251.9 2139.88   279.4 2151.26   284.8 2153.98   291.6  2156.4
   306.7 2163.57   316.5 2169.12   353.9 2187.26     394 2208.69   402.1 2212.62
#Mann= 3 ,-1,0
       0      .1       0   182.3    .045       0201.5888      .1       0
Bank Sta=182.3,201.5888
XS Rating Curve= 0 ,0
Exp/Cntr(USF)=0,0
Exp/Cntr=0.3,0.1

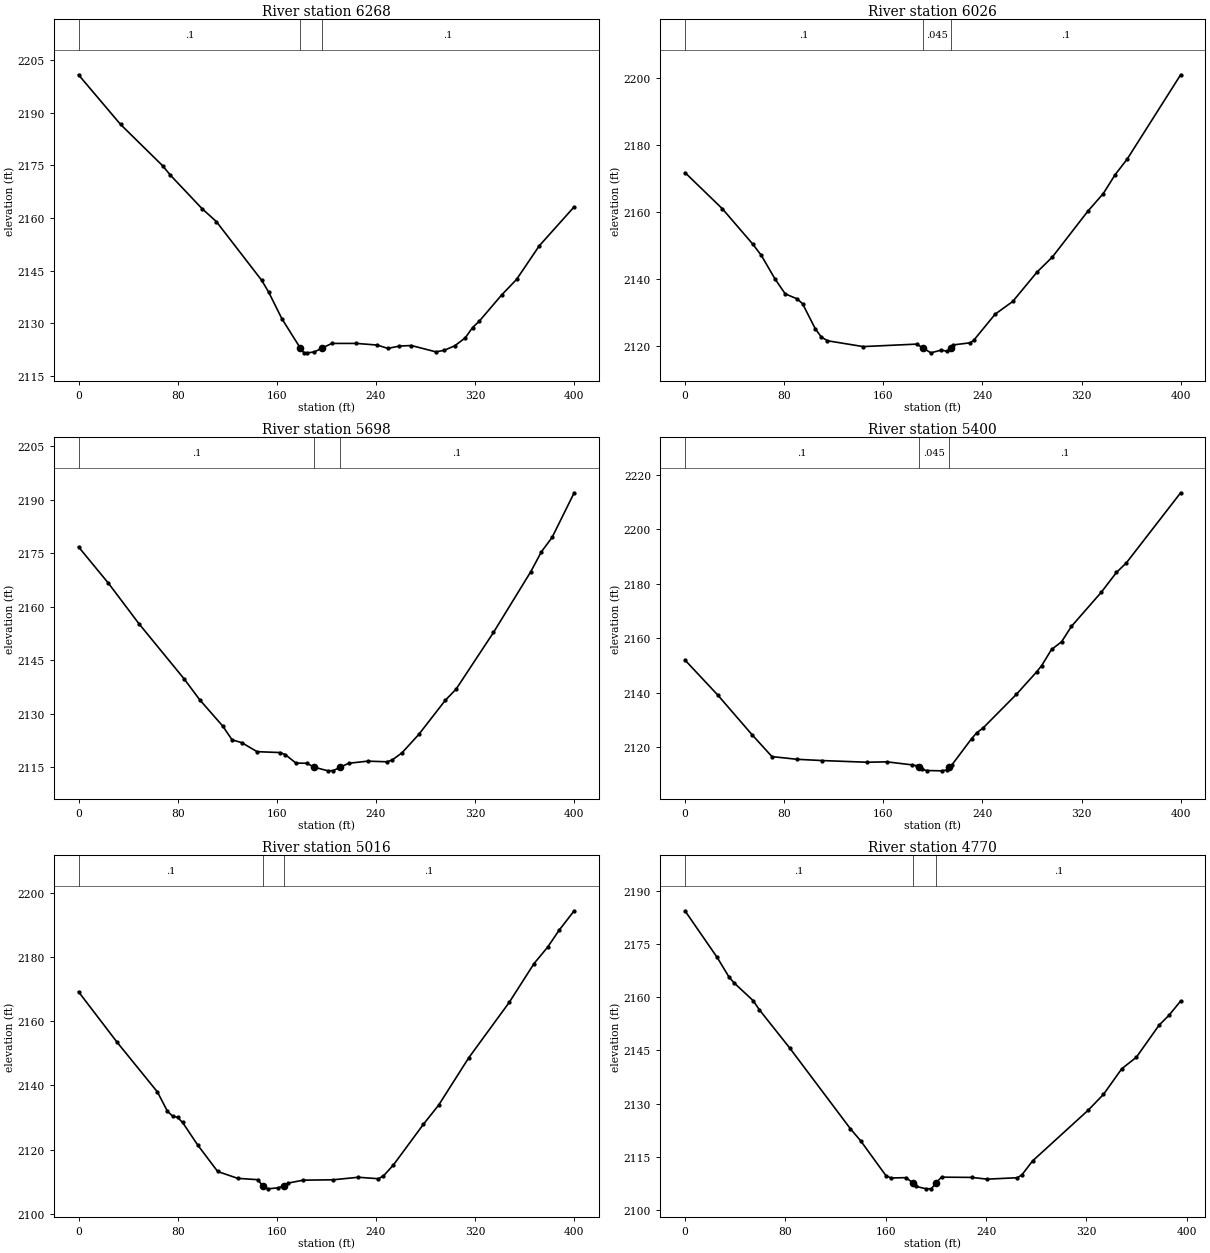
Type RM Length L Ch R = 1 ,6268    ,239.2,241.7,244.7
XS GIS Cut Line= 2
2206754.13883714420158.2571703952206459.35621093420428.633210904
#Sta/Elev= 30
       0 2200.89    33.9 2186.73    67.8 2174.96    74.2 2172.22    99.7 2162.68
   111.2 2159.01   147.8 2142.24   153.5 2138.83   164.1 2131.28     179 2122.89
   181.8  2121.6   184.6 2121.53   190.3 2121.78  196.262122.845   204.5 2124.22
   224.3 2124.22     241 2123.75   249.8 2122.79   258.8 2123.46   268.6 2123.62
   288.4 2121.81   295.1 2122.25   303.6 2123.53   312.1  2125.8     318 2128.75
   323.4 2130.56   341.6  2138.1   353.5 2142.48   371.8 2152.06     400  2163.2
#Mann= 3 ,-1,0
       0      .1       0     179    .045       0  196.26      .1       0
Bank Sta=179,196.26
XS Rating Curve= 0 ,0
Exp/Cntr(USF)=0,0
Exp/Cntr=0.3,0.1

Type RM Length L Ch R = 1 ,6026    ,322.5,327.9,328.6
XS GIS Cut Line= 2
2206583.06930347 420048.241102322206252.49156474420273.448470437
#Sta/Elev= 30
       0 2171.71    30.1 2160.92    54.6 2150.37    61.6 2146.95    72.7 2139.88
    80.9 2135.45    90.6 2133.94    94.9  2132.5   105.1 2125.05     110 2122.56
     115 2121.43   143.8 2119.69     187 2120.43   192.3  2119.2   198.5 2117.82
   206.8 2118.65   211.6 2118.28  214.352119.305   216.5 2120.19   230.2 2120.82
   233.1  2121.6   250.3 2129.38   264.5 2133.17   284.2    2142   296.4 2146.42
   325.2  2160.2   337.5 2165.39   347.1 2171.05   356.9 2175.75     400 2200.94
#Mann= 3 ,-1,0
       0      .1       0   192.3    .045       0  214.35      .1       0
Bank Sta=192.3,214.35
XS Rating Curve= 0 ,0
Exp/Cntr(USF)=0,0
Exp/Cntr=0.3,0.1

Type RM Length L Ch R = 1 ,5698    ,292.2,298.1,301.1
XS GIS Cut Line= 2
2206487.23124211419804.9876945382206115.65541477419953.080248489
#Sta/Elev= 30
       0 2176.79    24.1 2166.61    48.7 2155.26    85.1 2139.81    97.9 2133.86
   116.4 2126.52   123.9 2122.67   131.8 2121.85   144.1 2119.34   162.6 2119.09
   166.9 2118.51   175.5 2116.13   184.2 2116.09   190.3 2114.97   201.4 2113.96
   205.7 2114.03   211.22114.977     218 2116.08   233.4 2116.68   248.8  2116.5
     253 2116.96   261.1 2119.03   274.6 2124.17   296.1 2133.79   304.7 2136.87
   334.9 2152.79     365 2169.83   373.6 2175.43   382.2 2179.45     400 2191.96
#Mann= 3 ,-1,0
       0      .1       0   190.3    .045       0   211.2      .1       0
Bank Sta=190.3,211.2
XS Rating Curve= 0 ,0
Exp/Cntr(USF)=0,0
Exp/Cntr=0.3,0.1

Type RM Length L Ch R = 1 ,5400    ,378.6,384.2,388.4
XS GIS Cut Line= 2
2206389.93100088 419597.762975542205992.74061478 419645.08947122
#Sta/Elev= 30
       0 2152.06    26.3 2139.29    54.1 2124.66    70.2 2116.61    90.4 2115.62
   110.5 2115.16   146.8 2114.54     163 2114.68     183 2113.59   187.1 2113.23
  188.682112.712   191.1 2111.92   195.1  2111.5   207.2 2111.38   211.2 2111.69
   213.4 2112.66   215.3 2113.49   231.3 2123.19   235.4 2125.33   240.5 2127.08
   267.4 2139.44   283.7 2147.67   287.8 2149.98   295.8 2155.93   303.9 2158.76
   311.9 2164.43   336.1 2177.02   348.2 2184.21   356.3 2187.79     400 2213.47
#Mann= 3 ,-1,0
       0      .1       0  188.68    .045       0   213.4      .1       0
Bank Sta=188.68,213.4
XS Rating Curve= 0 ,0
Exp/Cntr(USF)=0,0
Exp/Cntr=0.3,0.1

Type RM Length L Ch R = 1 ,5016    ,244.5,245.5,244.4
XS GIS Cut Line= 2
2206431.06017912419288.3637171742206036.17817411419224.581257825
#Sta/Elev= 30
       0 2169.13    31.3 2153.34    63.7 2137.95    71.8 2131.92    75.9 2130.46
    79.9 2130.05      84 2128.46    96.1 2121.49   112.3 2113.21   128.5 2111.07
   144.7 2110.66   148.8 2108.64   152.8 2107.81   160.9 2108.12   165.8 2108.73
   169.2  2109.6   181.2  2110.5   205.5 2110.63   225.8 2111.41     242 2110.96
   246.1 2111.84   254.1 2115.22   278.4 2127.93   290.6 2133.84   314.9 2148.57
   347.6 2165.83   367.6 2177.89   378.6 2183.01   387.8 2188.24     400 2194.32
#Mann= 3 ,-1,0
       0      .1       0   148.8    .045       0   165.8      .1       0
Bank Sta=148.8,165.8
XS Rating Curve= 0 ,0
Exp/Cntr(USF)=0,0
Exp/Cntr=0.3,0.1

Type RM Length L Ch R = 1 ,4770    ,275.9,283.3,287.4
XS GIS Cut Line= 2
2206511.02354496419055.065782058 2206119.1075062419004.665196435
#Sta/Elev= 30
       0 2184.32    25.7 2171.16    35.1 2165.66    39.2 2163.99    54.3 2159.02
    59.3 2156.43    83.5 2145.66   131.9  2122.9     140 2119.54   160.2  2109.7
   164.2 2109.05   176.3 2109.14   181.6 2107.65   184.4 2106.65   192.4 2105.99
   196.5 2106.03   200.1 2107.71   204.5 2109.28   228.7 2109.21   240.8 2108.72
     265 2109.12   268.7 2109.99   277.1 2113.86   321.5 2128.17   333.6  2132.6
   348.2 2139.83   359.8 2143.05   377.9 2152.09     386 2154.95   395.1  2158.9
#Mann= 3 ,-1,0
       0      .1       0   181.6    .045       0   200.1      .1       0
Bank Sta=181.6,200.1
XS Rating Curve= 0 ,0
Exp/Cntr(USF)=0,0
Exp/Cntr=0.3,0.1

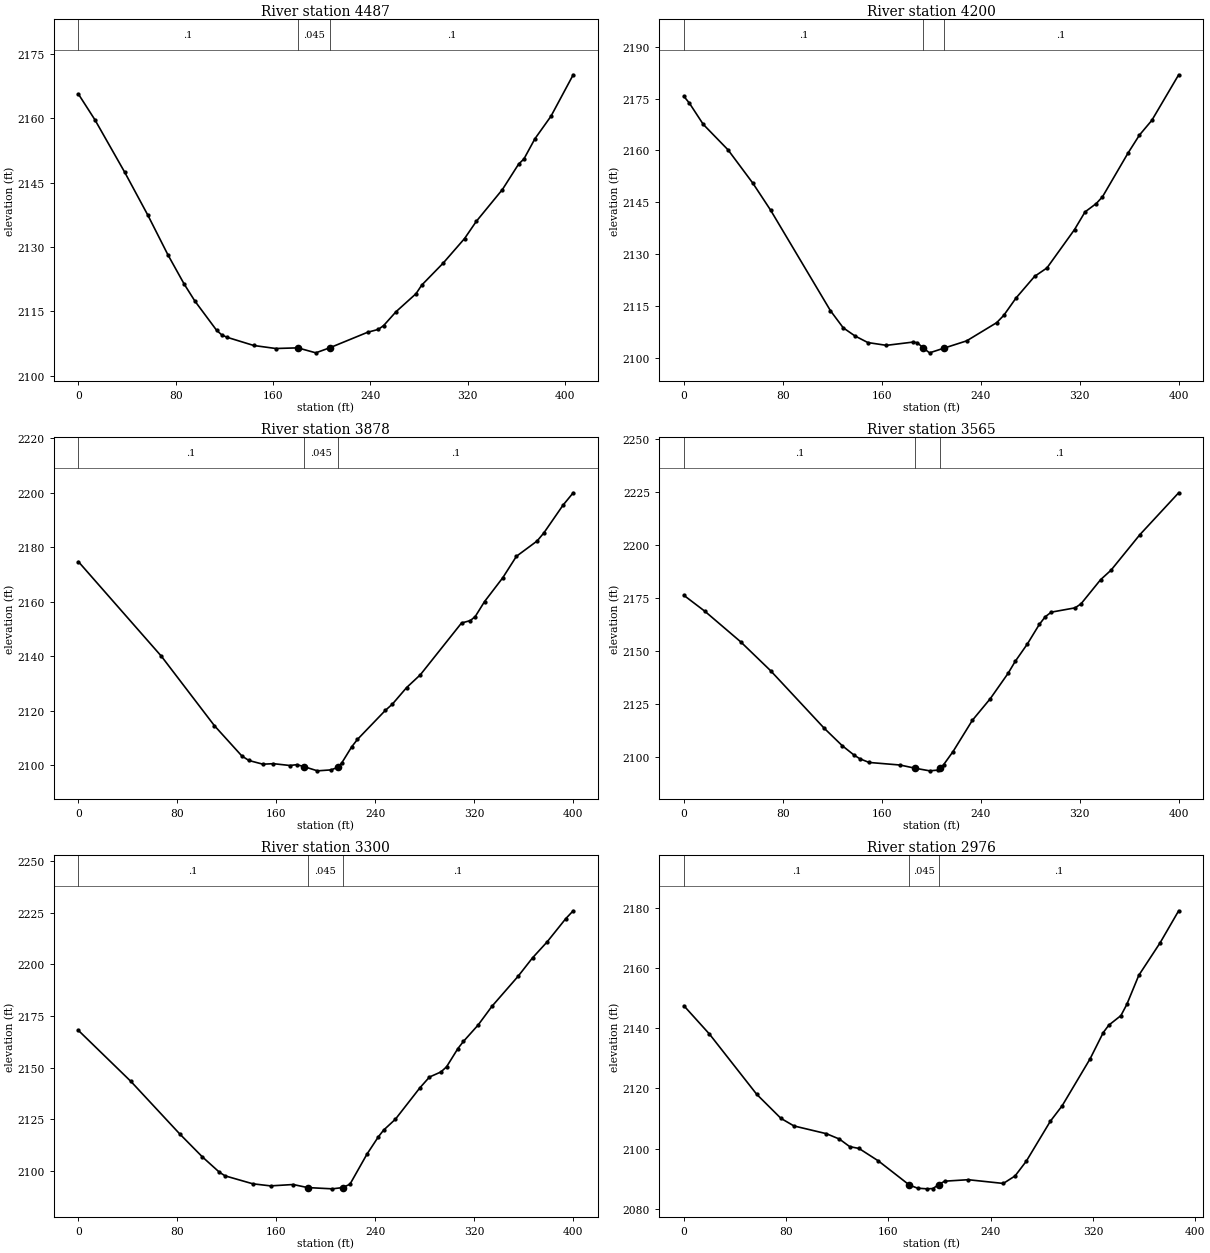
Type RM Length L Ch R = 1 ,4487    ,283.8,287,289.4
XS GIS Cut Line= 2
2206534.52310642418850.9878083752206167.63052059418675.452000677
#Sta/Elev= 30
       0  2165.6    13.5 2159.64    38.1 2147.37    57.1 2137.38    73.6 2128.15
    86.9 2121.37    95.7 2117.42   113.5 2110.63   117.9 2109.51   122.3 2108.97
   144.1 2107.07   162.2 2106.37   180.3 2106.52   195.1 2105.36   206.6 2106.54
   237.6 2110.14   246.5 2110.82   250.9 2111.72   261.1 2114.95   277.5 2119.14
   282.2 2121.14   299.7 2126.22   317.4 2131.98     327 2135.96   348.5 2143.39
   361.8  2149.3   366.2 2150.51   375.2  2155.2   388.4 2160.45   406.7 2170.11
#Mann= 3 ,-1,0
       0      .1       0   180.3    .045       0   206.6      .1       0
Bank Sta=180.3,206.6
XS Rating Curve= 0 ,0
Exp/Cntr(USF)=0,0
Exp/Cntr=0.3,0.1

Type RM Length L Ch R = 1 ,4200    ,318.9,322,323.4
XS GIS Cut Line= 2
2206651.39230587418635.8550623772206330.76956332418396.687637841
#Sta/Elev= 30
       0 2175.67     4.5 2173.66    15.6 2167.57    35.7 2160.16    55.7 2150.53
      70 2142.75   118.5 2113.56   128.8 2108.62   138.3 2106.26   148.7 2104.35
   163.7 2103.54   185.1 2104.48   188.7 2104.31   193.6 2102.73   198.6 2101.37
     210  2102.7   228.6 2104.84   252.9 2110.12   258.6 2112.23   268.5 2117.25
   283.5 2123.51   293.5 2125.96   315.8 2137.08   324.3 2142.19   333.4 2144.63
   338.4 2146.57     359 2159.21   368.3 2164.46   378.3 2168.72     400 2181.92
#Mann= 3 ,-1,0
       0      .1       0   193.6    .045       0     210      .1       0
Bank Sta=193.6,210
XS Rating Curve= 0 ,0
Exp/Cntr(USF)=0,0
Exp/Cntr=0.3,0.1

Type RM Length L Ch R = 1 ,3878    ,309.4,313.5,315.7
XS GIS Cut Line= 2
2206835.78623478418424.3963850782206558.50541139418136.099064628
#Sta/Elev= 30
       0 2174.66    67.1 2139.93   109.9 2114.47   132.1 2103.34   137.8 2101.68
   149.1 2100.32   157.6 2100.51     171 2099.84   176.5 2100.15   182.1 2099.46
   193.2 2097.88   204.3 2098.23   209.8 2099.22   212.9  2100.8   220.9 2106.69
   225.5 2109.39   248.1 2120.07   253.8 2122.37   265.3 2128.45   276.4 2133.15
   309.7 2152.16   316.8 2153.05   320.8 2154.54   328.3 2160.02     343 2168.75
   354.1 2176.66   370.8 2182.27   376.3 2185.26   391.8 2195.45     400 2199.98
#Mann= 3 ,-1,0
       0      .1       0   182.1    .045       0   209.8      .1       0
Bank Sta=182.1,209.8
XS Rating Curve= 0 ,0
Exp/Cntr(USF)=0,0
Exp/Cntr=0.3,0.1

Type RM Length L Ch R = 1 ,3565    ,262.8,264.5,266.1
XS GIS Cut Line= 2
 2207058.1084779418263.1398250792206833.94711821417931.851906761
#Sta/Elev= 30
       0  2176.4    16.9 2168.92    45.8 2154.54      70 2140.92   113.4 2113.75
   127.9 2105.56   137.6 2101.06   142.4  2099.3   149.7 2097.61   174.8 2096.39
   187.2 2094.85   198.7 2093.65   205.2    2094   207.3 2094.91     210 2096.58
   217.6 2102.76   233.2 2117.48   247.7 2127.69   262.1 2139.64   267.8 2145.23
   277.7  2153.5   287.3 2162.67   292.1  2166.3     297 2168.48   316.3 2170.52
   321.1 2172.44   336.9 2183.81   345.3 2188.27   368.6    2205     400 2224.78
#Mann= 3 ,-1,0
       0      .1       0   187.2    .045       0   207.3      .1       0
Bank Sta=187.2,207.3
XS Rating Curve= 0 ,0
Exp/Cntr(USF)=0,0
Exp/Cntr=0.3,0.1

Type RM Length L Ch R = 1 ,3300    ,321.5,324.5,324.6
XS GIS Cut Line= 2
2207268.96754888418132.4561187572207072.62772363 417783.95838129
#Sta/Elev= 30
       0 2167.97    42.4 2143.33    81.8 2117.98   100.2 2106.82   113.9 2099.44
   118.5 2097.67     141 2093.81   155.3 2092.81   173.6 2093.47  185.26 2091.99
   205.3 2091.38  213.55 2091.99   219.5 2093.61   233.3  2108.2   242.5 2116.57
   246.7 2119.77   256.3 2125.09   276.1 2140.28   283.8 2145.46     293  2147.9
   297.6 2150.39   306.8 2159.25   311.3 2162.71   323.1 2170.59   334.3 2179.66
   355.4 2194.15   367.1 2203.09   378.9  2210.8     394 2222.07     400 2225.86
#Mann= 3 ,0,0
       0      .1       0  185.26    .045       0  213.55      .1       0
Bank Sta=185.26,213.55
XS Rating Curve= 0 ,0
Exp/Cntr(USF)=0,0
Exp/Cntr=0.3,0.1

Type RM Length L Ch R = 1 ,2976    ,273.1,275.5,270.4
XS GIS Cut Line= 3
2207611.88789588417973.3118482532207483.12236938417872.168309979
2207372.95293764417677.814177895
#Sta/Elev= 30
       0 2147.42      20 2138.02    56.9 2118.07    75.9 2110.06    86.1 2107.54
   111.5 2104.97   121.7 2103.18   129.7 2100.68     137 2100.07   152.2 2095.92
   176.4 2087.93   182.8 2086.89   190.2 2086.67   194.8 2086.77   199.4 2088.09
     204 2089.21   222.4  2089.7   249.9 2088.46   259.1 2090.95   267.9 2095.86
   286.7 2109.11   295.9 2114.21   317.8 2129.82   328.1 2138.53   332.4 2140.98
   341.9 2144.16   346.5 2147.85   355.9 2157.53   372.5 2168.27   387.1 2178.95
#Mann= 3 ,-1,0
       0      .1       0   176.4    .045       0   199.4      .1       0
Bank Sta=176.4,199.4
XS Rating Curve= 0 ,0
Exp/Cntr(USF)=0,0
Exp/Cntr=0.3,0.1

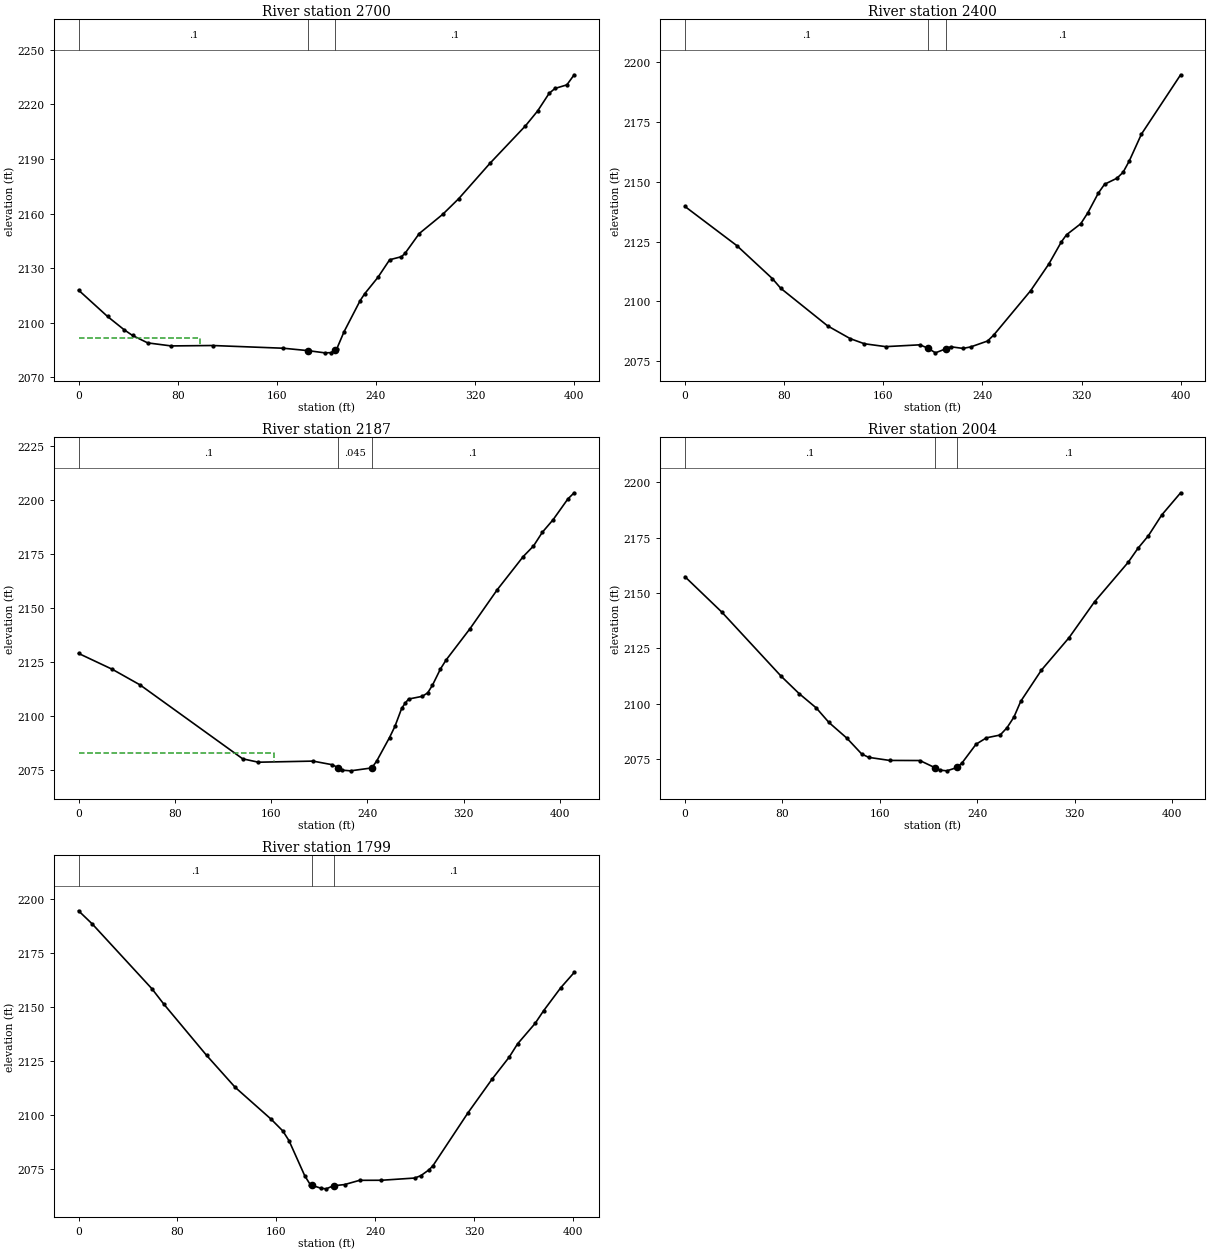
Type RM Length L Ch R = 1 ,2700    ,297.6,300,298.1
XS GIS Cut Line= 2
2207737.67387278417816.0152119272207520.36388221417480.193282929
#Sta/Elev= 30
       0 2117.89    23.4  2103.4    36.7 2096.14    43.6 2092.93    55.8 2088.86
    74.8 2087.18   108.2 2087.41   165.4 2085.91   185.4 2084.58   198.7 2083.38
   203.5 2083.47     207 2084.72   208.5  2085.7   214.3    2095   227.3 2112.12
     231 2115.93   241.6 2124.88   251.1 2134.58   260.6 2136.26   263.5 2138.09
     275 2149.01     294 2159.61   306.9 2168.23   332.1 2187.67   360.7 2208.24
   370.5 2216.41   379.8 2226.11   384.5  2228.8   394.1 2230.77     400 2236.32
#Mann= 3 ,-1,0
       0      .1       0   185.4    .045       0     207      .1       0
#XS Ineff= 2 , 0
           98.14 2091.29
Permanent Ineff=
       F       F
Bank Sta=185.4,207
XS Rating Curve= 0 ,0
Exp/Cntr(USF)=0,0
Exp/Cntr=0.3,0.1

Type RM Length L Ch R = 1 ,2400    ,214,213.1,210.9
XS GIS Cut Line= 2
2208026.02280905417713.8497455332207788.85308444417391.746467486
#Sta/Elev= 30
       0 2139.63    41.9 2123.27    70.5 2109.53    77.3 2105.47   115.1 2089.78
   133.4 2084.44   144.8 2082.31     162 2081.11   189.6 2081.87   196.3 2080.41
   202.1 2078.52   210.6 2080.22   214.4 2081.06   224.4 2080.37   230.7 2081.01
   244.2 2083.46   249.2 2085.97     279 2104.51   293.6 2115.59   303.8  2124.9
   307.9 2127.82   319.4 2132.43   325.1 2136.99   333.6 2145.24   338.6 2148.91
   348.5 2151.41   353.5 2153.86   358.5 2158.59   368.4 2169.88     400 2194.63
#Mann= 3 ,-1,0
       0      .1       0   196.3    .045       0   210.6      .1       0
Bank Sta=196.3,210.6
XS Rating Curve= 0 ,0
Exp/Cntr(USF)=0,0
Exp/Cntr=0.3,0.1

Type RM Length L Ch R = 1 ,2187    ,184.2,183,181.5
XS GIS Cut Line= 3
2208248.78462752417547.9063555482208116.24907894417473.559947496
2207946.03805134417277.288534917
#Sta/Elev= 30
       0 2128.96    28.2 2121.57    51.1  2114.4   136.4 2080.22   149.4 2078.65
   194.8 2079.16   210.7  2077.5     216 2076.05   219.2 2074.97     226 2074.66
   243.7 2076.01   247.8 2079.26   258.4 2090.07   262.9 2095.23   268.5 2103.56
   271.4 2105.94   274.2 2107.85   285.6 2109.11   290.1 2110.71   294.1 2114.29
   300.7 2121.76   305.4 2125.91   325.3 2140.42   347.9 2158.41   369.5 2173.75
     378 2178.61   385.4 2184.99   394.3 2190.77   406.6 2200.39   411.8 2203.22
#Mann= 3 ,-1,0
       0      .1       0     216    .045       0   243.7      .1       0
#XS Ineff= 2 , 0
          162.53 2082.72
Permanent Ineff=
       F       F
Bank Sta=216,243.7
XS Rating Curve= 0 ,0
Exp/Cntr(USF)=0,0
Exp/Cntr=0.3,0.1

Type RM Length L Ch R = 1 ,2004    ,209.6,204.7,201.3
XS GIS Cut Line= 3
2208372.60748687417423.001971342 2208223.7164396417317.469305965
2208060.91798681417162.851679947
#Sta/Elev= 30
       0 2157.34    30.3 2141.32      79 2112.34    93.7 2104.52   107.8 2098.03
   118.2 2091.46   132.9 2084.38   145.1 2077.22   150.8 2075.69     168  2074.3
   192.9 2074.25     205 2071.08   209.4 2069.93     215 2069.59   223.6 2071.13
   227.6 2073.24     239 2081.62   247.5 2084.51   258.8 2085.78   264.4 2089.05
   270.1 2093.87   275.7 2101.02   292.7 2115.14   315.4  2129.8   336.3 2146.01
   363.9 2163.84   371.9 2170.15   380.5 2175.86   391.5 2185.26     407 2195.29
#Mann= 3 ,-1,0
       0      .1       0     205    .045       0   223.6      .1       0
Bank Sta=205,223.6
XS Rating Curve= 0 ,0
Exp/Cntr(USF)=0,0
Exp/Cntr=0.3,0.1

Type RM Length L Ch R = 1 ,1799    ,298.5,299.1,299.3
XS GIS Cut Line= 4
2208501.42540437417247.8697935712208366.88090813417157.125101206
2208271.16523488417111.3124712752208162.78735421417034.974817153
#Sta/Elev= 30
       0 2194.42    11.2 2188.28    59.4 2158.33    69.1 2151.17   103.7 2127.46
   126.7 2112.75   155.9 2097.94   165.3 2092.53   170.3 2088.04     183 2071.84
   187.5 2067.69189.00812067.339   196.3 2066.01   200.3 2065.75206.29352067.169
   215.3 2067.73   227.4 2069.69   245.1 2069.72   272.1 2070.75     277 2071.87
   283.6 2074.57   286.7 2076.41   315.1 2100.94   334.6 2116.53   348.5 2126.75
   355.2 2132.83   369.4  2142.3   376.3 2148.19   390.2 2158.85     401 2165.86
#Mann= 3 ,-1,0
       0      .1       0189.0081    .045       0206.2935      .1       0
Bank Sta=189.0081,206.2935
XS Rating Curve= 0 ,0
Exp/Cntr(USF)=0,0
Exp/Cntr=0.3,0.1