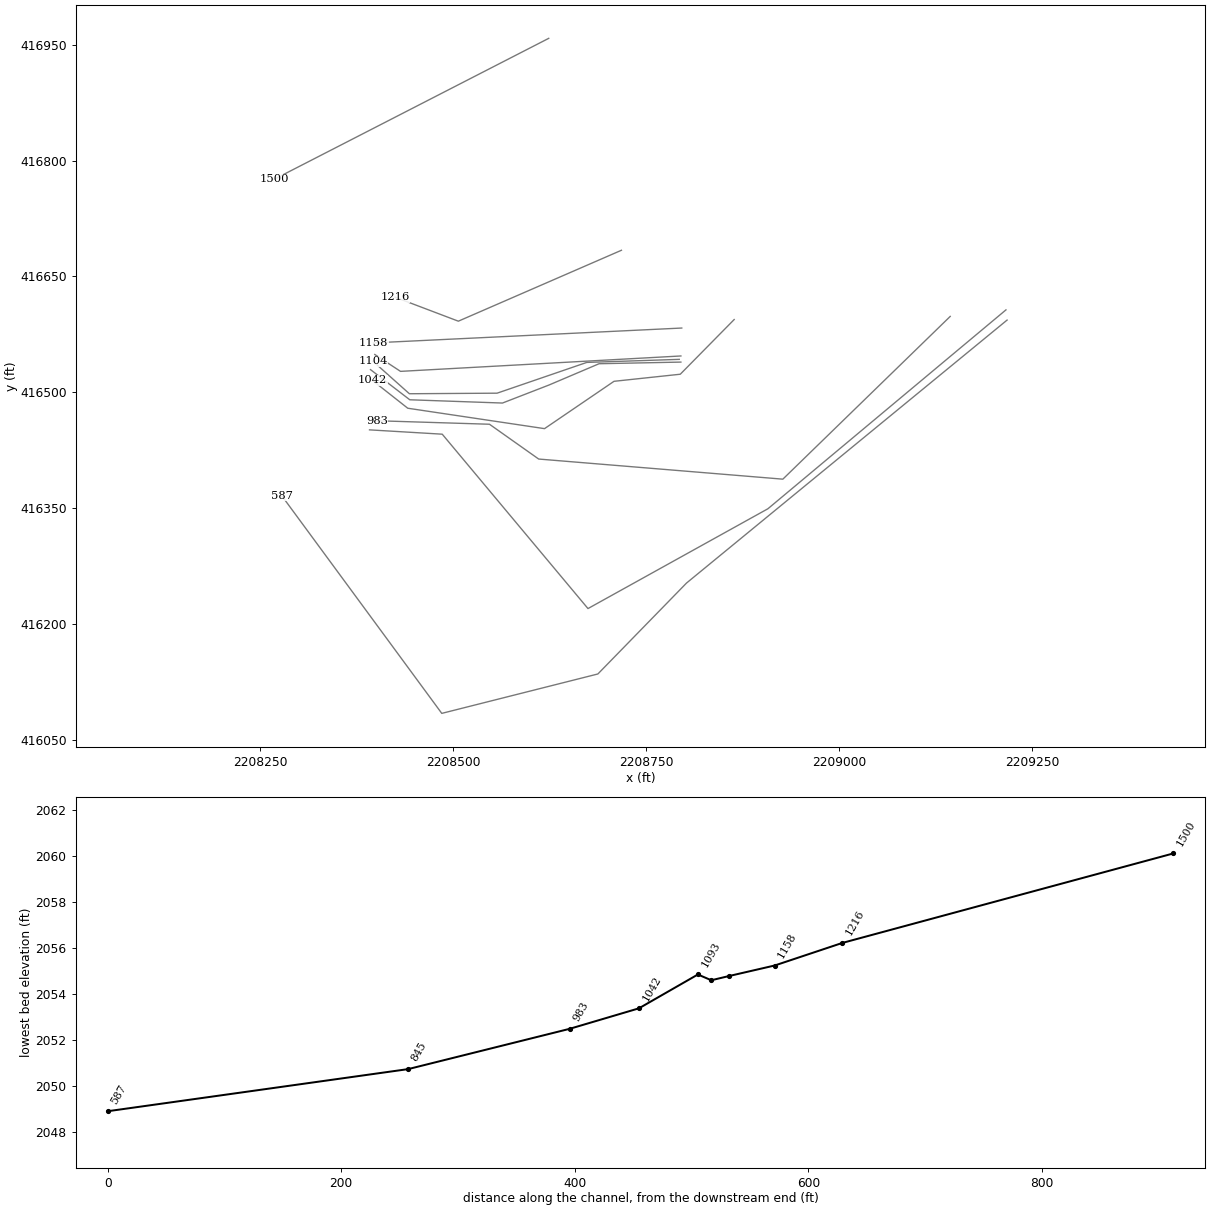
HEC-RAS study STVNSHLRN.prj: STVNSHLRN

--- STVNSHLRN.g01 (geometry) --- (continued)

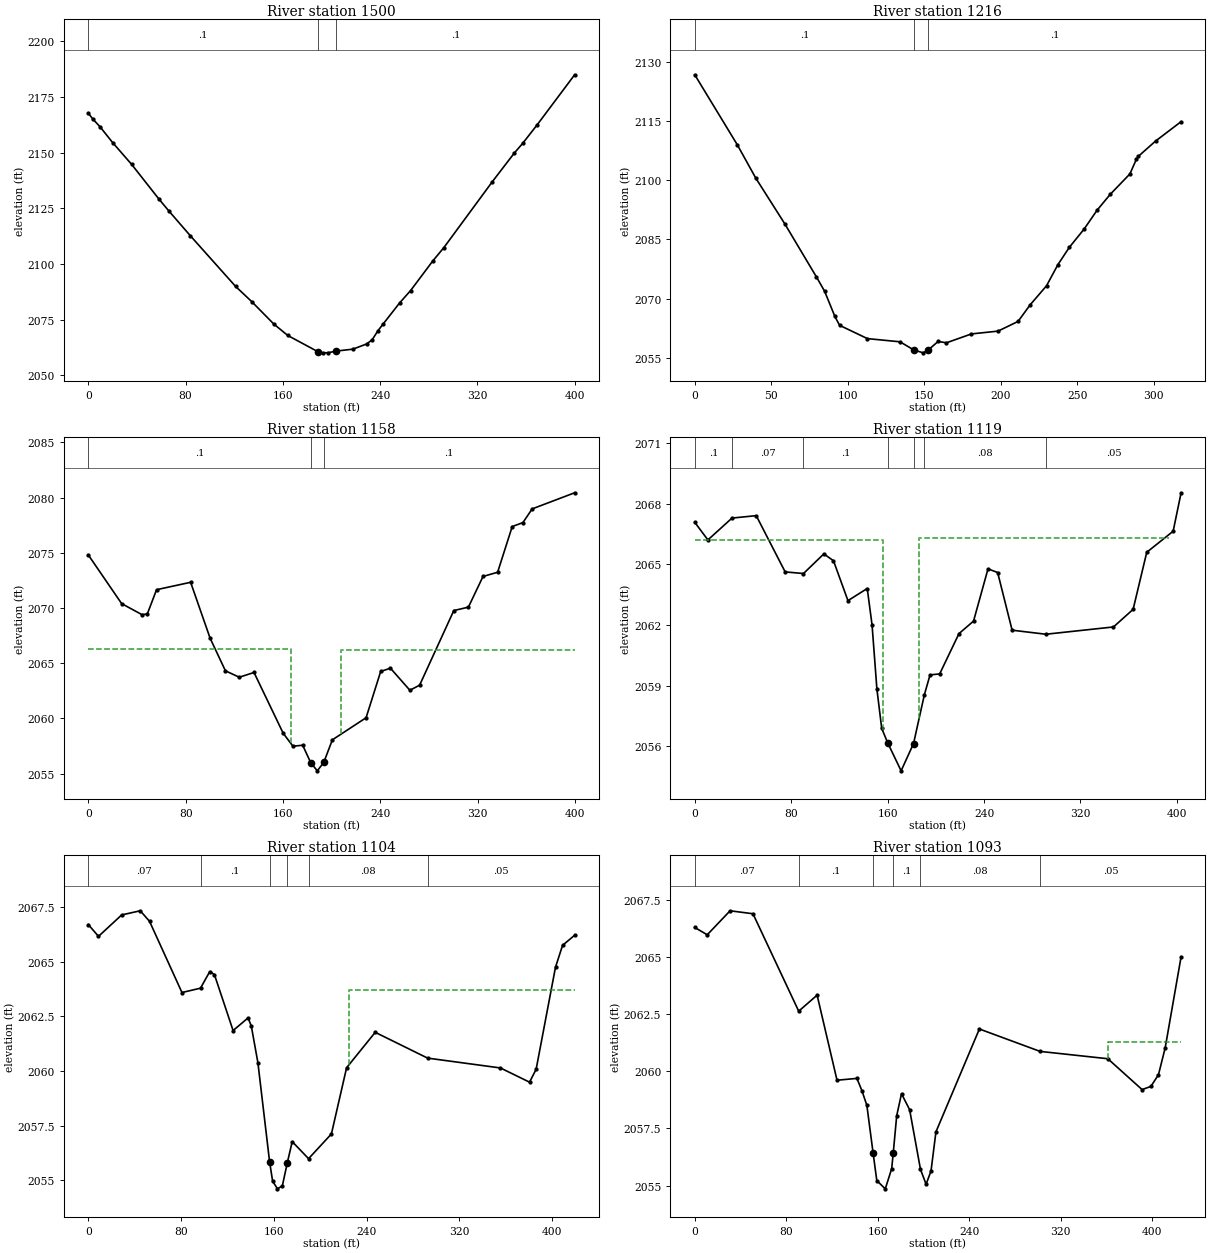
Type RM Length L Ch R = 1 ,1500    ,283.8,283.6,282.8
XS GIS Cut Line= 2
2208623.91256436416958.3277401482208268.07381676416775.629120264
#Sta/Elev= 30
       0 2167.79     3.6 2165.24     9.6 2161.71      20 2154.59    35.7 2144.75
    58.2 2129.13      66 2124.03    83.8  2112.8   121.1 2089.99   134.4 2083.14
   152.6 2073.05   164.1 2067.91   188.6 2060.71   193.1 2060.12   197.5 2060.19
   203.9 2060.92   217.5 2061.76     229 2064.12   233.5 2066.01   238.3 2070.11
   242.5 2073.07     256 2082.51   265.1 2088.11   283.2  2101.3   292.5 2107.44
   332.4 2137.07   350.4 2149.89   357.2 2154.18   369.1  2162.5     400 2185.04
#Mann= 3 ,-1,0
       0      .1       0   188.6    .045       0   203.9      .1       0
Bank Sta=188.6,203.9
XS Rating Curve= 0 ,0
Exp/Cntr(USF)=0,0
Exp/Cntr=0.3,0.1

Type RM Length L Ch R = 1 ,1216    ,61,57.9,53.4
BEGIN DESCRIPTION:
Structure XS 4
END DESCRIPTION:
XS GIS Cut Line= 3
2208718.07390091416683.8453831962208506.83219157416592.001161744
2208424.87888627416623.086898235
#Sta/Elev= 30
       0 2126.78    27.8 2109.03    39.9 2100.56    58.8    2089    79.5 2075.53
    84.9 2071.86    91.6 2065.48    94.7 2063.21   112.9 2059.84   134.2 2059.03
   143.3 2056.95   149.4 2056.23   152.4 2056.87   159.1 2059.11   164.6 2058.78
   180.9 2061.03   198.3 2061.74   211.4  2064.2   219.3 2068.41     230 2073.24
   237.5 2078.64   244.9 2082.99   254.6 2087.64   263.1 2092.44   271.7 2096.46
   284.5 2101.61   288.8 2105.38   290.1 2106.11   301.3 2109.96     318 2114.89
#Mann= 3 ,-1,0
       0      .1       0   143.3    .045       0   152.4      .1       0
Bank Sta=143.3,152.4
XS Rating Curve= 0 ,0
Exp/Cntr(USF)=0,0
Exp/Cntr=0.5,0.3

Type RM Length L Ch R = 1 ,1158    ,41.4,39.3,38.5
BEGIN DESCRIPTION:
Structure XS 3; 15.3 ft between structure and xs
END DESCRIPTION:
XS GIS Cut Line= 2
2208796.20663846416583.1197164472208396.92774694416563.889723692
#Sta/Elev= 30
       0 2074.81    27.4  2070.4    44.1  2069.4    48.5 2069.46    56.1 2071.66
    84.1 2072.33   100.1 2067.27   112.7 2064.31   124.1 2063.73   136.2 2064.16
   160.2 2058.65   168.2 2057.48   176.2 2057.57  182.742056.002   188.2 2055.25
  193.532056.017   200.6 2058.06   228.3 2060.06   240.3 2064.25   248.3 2064.55
   264.3 2062.55   272.3 2063.01   300.4 2069.77   312.4 2070.08   324.4 2072.86
   336.4 2073.24   348.4 2077.38   357.2 2077.74   364.8 2078.98   399.7 2080.44
#Mann= 3 ,-1,0
       0      .1       0  182.74    .045       0  193.53      .1       0
#XS Ineff= 2 , 0
             167  2066.3     208          2066.2
Permanent Ineff=
       F       F
Bank Sta=182.74,193.53
XS Rating Curve= 0 ,0
Exp/Cntr(USF)=0,0
Exp/Cntr=0.5,0.3

Type RM Length L Ch R = 1 ,1119    ,10.9,14.9,20
BEGIN DESCRIPTION:
Structure XS 2; 11.6 ft between structure and xs
END DESCRIPTION:
XS GIS Cut Line= 3
2208795.08174812416546.9467586932208431.94360785416526.993532315
2208398.61990895416548.853941922
#Sta/Elev= 30
       0 2067.07    10.9  2066.2    30.9 2067.28      51  2067.4      75 2064.62
    90.2 2064.54   107.1 2065.51   115.1 2065.17   127.1  2063.2   143.1  2063.8
   147.1    2062   151.1 2058.84   155.1 2056.89   160.1 2056.17   171.2 2054.79
  181.52 2056.14   190.5 2058.55   195.2 2059.53   203.2 2059.58   219.2 2061.57
   231.3 2062.19   243.3 2064.77   251.3 2064.59   263.3 2061.74   291.3 2061.54
   347.4  2061.9   363.7 2062.77     375 2065.59   396.9 2066.63   403.5 2068.53
#Mann= 7 ,-1,0
       0      .1       0    30.9     .07       0    90.2      .1       0
   160.1    .045       0  181.52      .1       0   190.5     .08       0
   291.3     .05       0
#XS Ineff= 2 ,-1
       0     156  2066.2     186   393.5  2066.3
Permanent Ineff=
       F       F
Bank Sta=160.1,181.52
XS Rating Curve= 0 ,0
Exp/Cntr(USF)=0,0
Exp/Cntr=0.5,0.3

Type RM Length L Ch R = 1 ,1104    ,10.2,11.5,12
BEGIN DESCRIPTION:
Structure XS 4/1
END DESCRIPTION:
XS GIS Cut Line= 5
2208792.96226609416542.5465809622208673.20202597416538.590519151
2208556.99326636 416498.743952272208443.41871029416498.025863635
2208396.22992934416540.134900404
#Sta/Elev= 30
       0  2066.7     8.8 2066.16    28.8 2067.14    44.8 2067.33    52.8 2066.85
    80.8 2063.59    96.8 2063.79   104.8 2064.55   108.8 2064.41   124.9 2061.85
   137.8 2062.43   140.6 2062.06   146.3 2060.38   156.4 2055.84     159 2054.96
   163.2 2054.61   167.4 2054.75   171.7 2055.81   175.9 2056.77     190 2055.99
   209.7 2057.12   222.8 2060.15   247.5 2061.77   292.7 2060.59   355.5 2060.14
   380.6 2059.49   386.3 2060.08     403 2064.75   409.1 2065.75   419.5 2066.21
#Mann= 6 ,-1,0
       0     .07       0    96.8      .1       0   156.4    .045       0
   171.7      .1       0     190     .08       0   292.7     .05       0
#XS Ineff= 2 , 0
                             225         2063.69
Permanent Ineff=
       F       F
Bank Sta=156.4,171.7
XS Rating Curve= 0 ,0
Exp/Cntr(USF)=0,0
Exp/Cntr=0.5,0.3

Type RM Length L Ch R = 1 ,1093    ,49.6,50.5,51.5
BEGIN DESCRIPTION:
Structure XS 3; 7.2 ft between structure and xs
END DESCRIPTION:
XS GIS Cut Line= 6
2208795.08174812416539.0141109062208689.10764645416536.894628873
2208624.23377187416509.3170476322208563.95855916416485.970406377
2208443.94030586 416490.201930152208393.07738102416529.254865429
#Sta/Elev= 30
       0 2066.29    10.9 2065.97    30.9 2067.02    50.9 2066.89    90.9 2062.63
     107 2063.33   124.4 2059.61   141.8 2059.69   146.2 2059.15   150.5 2058.51
  155.95 2056.43   159.2 2055.22   166.6 2054.86   172.2 2055.74   173.6 2056.44
   176.6 2058.06   180.8 2059.02   187.9 2058.32   197.4 2055.71   202.3 2055.06
   206.6 2055.64   210.9 2057.35   248.9 2061.85     302 2060.87   361.2 2060.55
   391.2  2059.2   398.9 2059.34   405.5 2059.85   411.4 2061.03   425.3 2065.01
#Mann= 6 ,-1,0
       0     .07       0    90.9      .1       0  155.95    .045       0
   173.6      .1       0   197.4     .08       0     302     .05       0
#XS Ineff= 3 ,-1
       0     148  2057.6     180  361.13  2055.6  361.13   425.3 2061.28
Permanent Ineff=
       F       F       F
Bank Sta=155.95,173.6
XS Rating Curve= 0 ,0
Exp/Cntr(USF)=0,0
Exp/Cntr=0.5,0.3

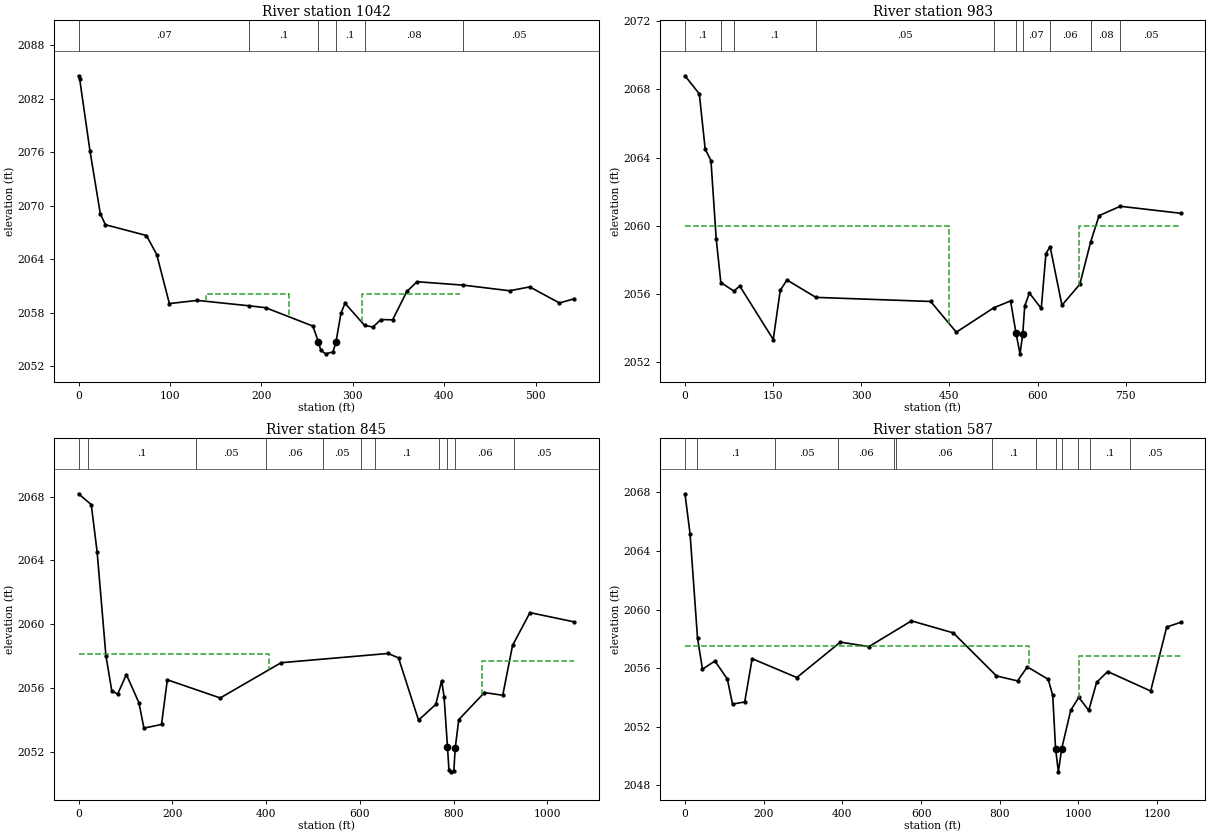
Type RM Length L Ch R = 1 ,1042    ,66.1,59.3,53
BEGIN DESCRIPTION:
Structure XS 2; 9.7 ft between structure and xs
END DESCRIPTION:
XS GIS Cut Line= 6
  2208864.086143 416594.115472432208794.27169396416523.292426261
2208708.45909583416514.1259201172208618.45824533416452.821841544
2208441.33232803 416479.248423272208395.64159827 416515.24634634
#Sta/Elev= 30
       0 2084.55     1.3 2084.17    12.5 2076.16    23.8 2069.11    29.4 2067.86
    74.3 2066.65    85.6 2064.51    99.4 2059.02   129.7 2059.38   186.1 2058.78
   204.7 2058.56   256.4  2056.5   262.3 2054.76   265.1 2053.78   270.3 2053.39
   278.3  2053.6  281.632054.715   287.1 2057.93   291.5 2059.06     313 2056.57
   322.1  2056.4   330.8 2057.23   343.6  2057.2   359.2 2060.39   370.4 2061.47
   420.9 2061.09   471.5 2060.46   493.6 2060.89   526.1 2059.09   542.2 2059.56
#Mann= 6 ,-1,0
       0     .07       0   186.1      .1       0   262.3    .045       0
  281.63      .1       0     313     .08       0   420.9     .05       0
#XS Ineff= 4 ,-1
  139.32  230.16 2060.11  230.16     259  2055.6     285     310  2055.6
     310  417.64 2060.05
Permanent Ineff=
       F       F       F       F
Bank Sta=262.3,281.63
XS Rating Curve= 0 ,0
Exp/Cntr(USF)=0,0
Exp/Cntr=0.5,0.3

Type RM Length L Ch R = 1 ,983     ,145.8,138.3,127.3
BEGIN DESCRIPTION:
Structure XS 1
END DESCRIPTION:
XS GIS Cut Line= 5
2209143.87927484416598.1678760692208927.11856232416387.386955875
2208610.90301983416413.440115208 2208547.1524507416458.516275205
2208401.43948617416463.048055979
#Sta/Elev= 30
       0  2068.8    24.4 2067.74    34.4  2064.5    44.2 2063.83    53.1 2059.26
      61 2056.68    83.3 2056.18    93.2 2056.48   150.2 2053.34   162.1 2056.22
   173.5 2056.83   222.8 2055.81     418 2055.57   461.8 2053.77   525.5  2055.2
   554.1  2055.6563.34882053.708   570.2  2052.5   574.8 2053.66   578.2 2055.31
   586.2 2056.06   606.3 2055.16   614.3 2058.38   621.4 2058.78   641.5 2055.35
     672 2056.58   690.3 2059.05   704.7  2060.6   740.7 2061.15   843.5 2060.74
#Mann= 10 ,-1,0
       0      .1       0      61     .07       0    83.3      .1       0
   222.8     .05       0   525.5     .07       0563.3488    .045       0
   574.8     .07       0   621.4     .06       0   690.3     .08       0
   740.7     .05       0
#XS Ineff= 2 , 0
             450    2060     670            2060
Permanent Ineff=
       F       F
Bank Sta=563.3488,574.8
XS Rating Curve= 0 ,0
Exp/Cntr(USF)=0,0
Exp/Cntr=0.3,0.1

Type RM Length L Ch R = 1 ,845     ,259.5,257.3,252.6
XS GIS Cut Line= 5
2209216.08894964416606.6397781872208907.76173067416349.045600927
 2208674.7251118416219.7917111832208485.97766213416445.637372349
2208391.80654266416451.235944054
#Sta/Elev= 30
       0 2068.18    27.2  2067.5    39.7 2064.53    58.4 2058.04    70.9 2055.83
    83.4 2055.62   102.1 2056.85   128.8 2055.08   139.5 2053.49     177 2053.72
   189.4 2056.52   302.2 2055.38   431.9 2057.59   660.3 2058.17   682.4 2057.89
     725 2053.99   761.9 2054.98   774.3 2056.46   779.5 2055.47  786.75 2052.32
     790 2050.84   795.2 2050.75   800.4 2050.83   803.2 2052.22   810.8 2054.02
   865.6 2055.72   904.6 2055.55   925.5 2058.67   962.6 2060.73  1056.9 2060.15
#Mann= 11 ,-1,0
       0     .06       0      20      .1       0     250     .05       0
     400     .06       0  521.77     .05       0  601.77     .06       0
  631.77      .1       0  768.25     .06       0  786.75    .045       0
   803.2     .06       0  928.25     .05       0
#XS Ineff= 2 , 0
          406.31 2058.13  860.44         2057.67
Permanent Ineff=
       F       F
Bank Sta=786.75,803.2
XS Rating Curve= 0 ,0
Exp/Cntr(USF)=0,0
Exp/Cntr=0.3,0.1

Type RM Length L Ch R = 1 ,587     ,,,
XS GIS Cut Line= 5
2209217.54831992416593.4279353632208802.38478477416252.856430173
 2208687.5523176 416135.079540772208485.36865746416084.042888695
2208278.27762693416365.725949184
#Sta/Elev= 30
       0 2067.91      13 2065.15    31.9 2058.04    44.5 2055.93    76.1 2056.49
   107.6 2055.26   120.8 2053.55   151.8 2053.69   170.7 2056.65   284.2 2055.36
     395 2057.78   467.3 2057.47   575.6 2059.23   681.8 2058.41   791.6 2055.47
   845.2 2055.13     870 2056.09   923.1 2055.24   934.6 2054.14  941.722050.511
   948.9 2048.92   957.4 2050.51   980.3 2053.12  1000.8 2054.01  1026.1 2053.11
  1046.1 2055.03  1074.1 2055.77  1183.5 2054.44  1224.2 2058.81  1259.6 2059.13
#Mann= 13 ,-1,0
       0     .06       0      30      .1       0     230     .05       0
     390     .06       0     530     .05       0  536.98     .06       0
  781.47      .1       0  891.47     .07       0  941.72    .045       0
   957.4     .07       0    1000     .06       0    1030      .1       0
    1130     .05       0
#XS Ineff= 2 , 0
          874.78 2057.53 1000.49         2056.86
Permanent Ineff=
       F       F
Bank Sta=941.72,957.4
XS Rating Curve= 0 ,0
Exp/Cntr(USF)=0,0
Exp/Cntr=0.3,0.1
LCMann Table=0

Chan Stop Cuts=-1
Use User Specified Reach Order=0
Composite Channel Slope=5